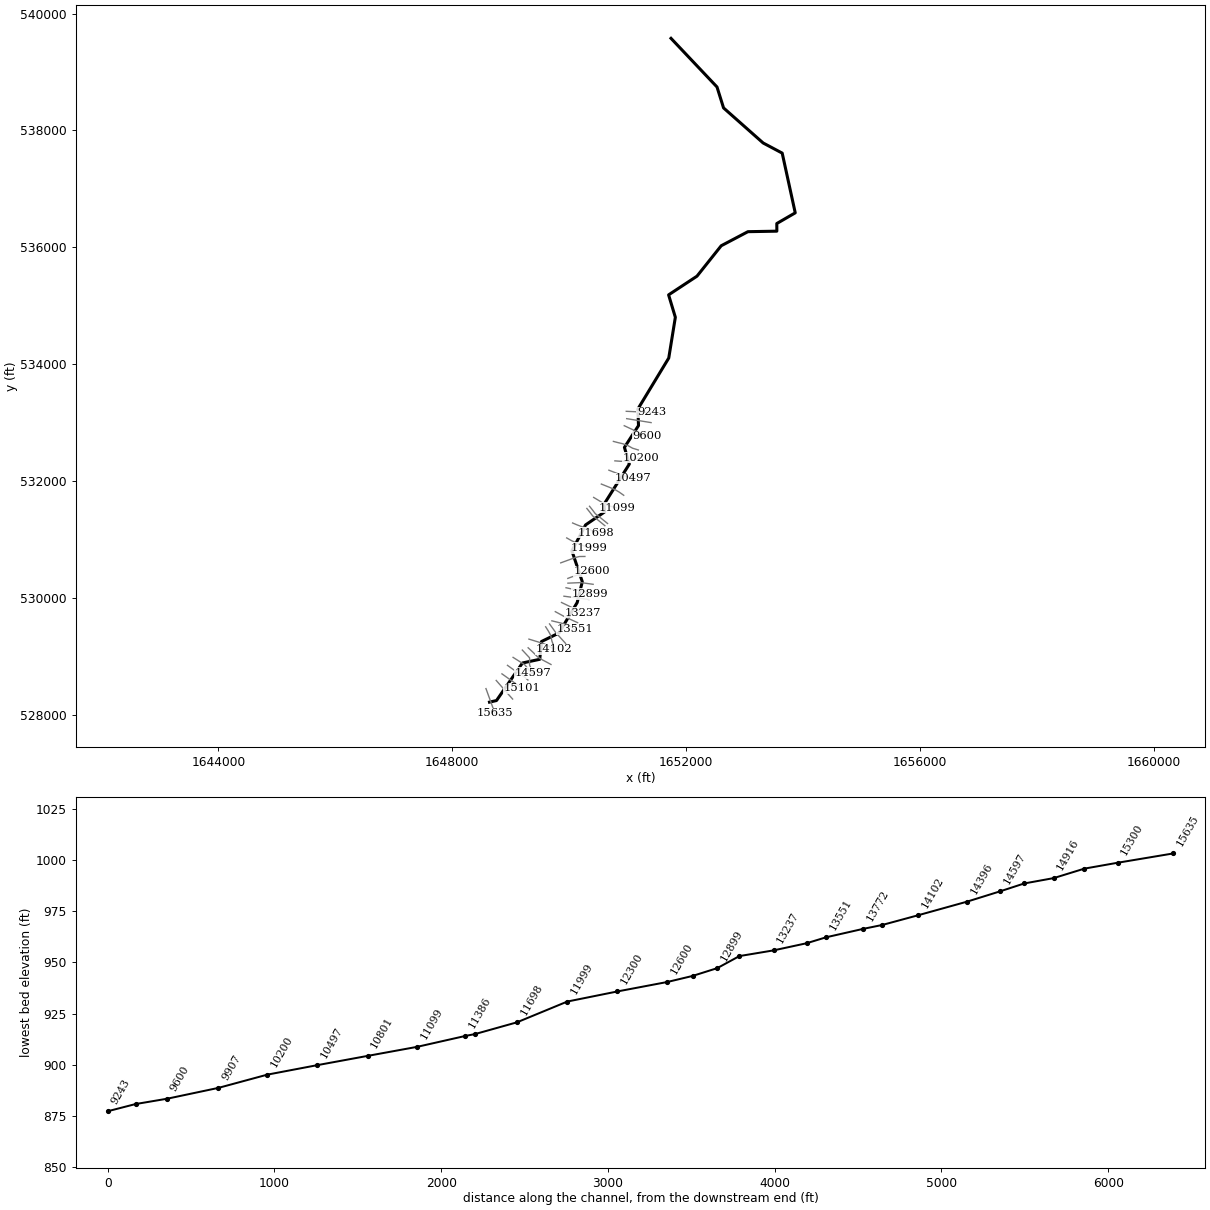
--- BurchRnI.prj (project) ---

Proj Title=BurchRnI
Current Plan=p01
Default Exp/Contr=0,0
English Units
Geom File=g01
Flow File=f01
Plan File=p01
BEGIN DESCRIPTION:
---------- MODELED AS PART OF WVEM CTP PROGRAM, 2025----------
Stream Name: Burch Run I
Flood Zone: AFH
Marshall County, WV
HEC-RAS Version: RAS 6.6
Vertical Datum: NAVD88
Projection: NAD 1983 StatePlane West Virginia N FIPS 4701 (US Feet)
Terrain: 1-meter West Virginia FEMA R3 South Central (collected 2018-2019)
Land Use: 2024 NLCD
Hydrologic Method:
Duda et al., "Estimation of magnitude and frequency of floods for rural, unregulated streams in and near Virginia and West Virginia." September 8, 2025.
Additional Model Notes:
None
END DESCRIPTION:
DSS Export Rating Curves= 0
DSS Export Rating Curve Sorted= 0
DSS Export Volume Flow Curves= 0
DXF OffsetX= 0
DXF OffsetY= 0
DXF ScaleX= 0
DXF ScaleY= 0

--- BurchRnI.p01 (plan) ---

Plan Title=Floodplain
Program Version=6.60
Short Identifier=Floodplain
Geom File=g01
Flow File=f01
Subcritical Flow
K Sum by GR= 0
Std Step Tol= 0.01
Critical Tol= 0.01
Num of Std Step Trials= 20
Max Error Tol= 0.3
Flow Tol Ratio= 0.001
Split Flow NTrial= 30
Split Flow Tol= 0.02
Split Flow Ratio= 0.02
Log Output Level= 0
Friction Slope Method= 1
Unsteady Friction Slope Method= 2
Unsteady Bridges Friction Slope Method= 1
Parabolic Critical Depth
Global Vel Dist= 0 , 0 , 0
Global Log Level= 0
CheckData=False
Encroach Param=-1 ,0,0, 0
Flow Ratio Tolerance=0.1
Flow Ratio Min Ratio=0.5
Flow Ratio Max Ratio=4
Flow Ratio Max Iterations= 10
Mapping Interval=1HOUR
Computation Time Step Use Courant=        0
Computation Time Step Use Time Series=    0
Computation Time Step Count To Double=0
Computation Time Step Max Doubling=0
Computation Time Step Max Halving=0
Computation Time Step Residence Courant=0
Run HTab= 0
Run UNet= 0
Run Sediment= 0
Run PostProcess= 0
Run WQNet= 0
Run RASMapper=-1
UNET Theta= 0
UNET Theta Warmup= 0
UNET ZTol= 0
UNET ZSATol= 0
UNET MxIter= 0
UNET Max Iter WO Improvement= 0
UNET MaxInSteps= 0
UNET DtIC= 0
UNET DtMin= 0
UNET MaxCRTS= 0
UNET WFStab= 0
UNET SFStab= 0
UNET WFX= 1
UNET SFX= 1
UNET Gravity=32.17405
UNET 1D Methodology=Finite Difference
UNET DSS MLevel= 1
UNET Pardiso=0
UNET DZMax Abort= 0
UNET Use Existing IB Tables= 0
UNET Froude Reduction=False
UNET Froude Limit= 0
UNET Froude Power= 0
UNET D1 Cores= 0
UNET WindReference=Eulerian
UNET WindDragFormulation=Hsu (1988)
UNET D2 Coriolis=0
UNET D2 Cores= 0
UNET D2 Theta= 1
UNET D2 Theta Warmup= 1
UNET D2 Z Tol= 0.01
UNET D2 Volume Tol= 0.01
UNET D2 Max Iterations= 20
UNET D2 Advanced Convergence=0
UNET D2 WS Max Tol=0.15
UNET D2 WS RMS Tol=0.002
UNET D2 WS Stall Tol=1
UNET D2 Equation= 0
UNET D2 RampUpFraction=0.1
UNET D2 TimeSlices= 1
UNET D2 Turbulence Formulation=Non-Conservative (original)
UNET D2 Eddy Viscosity=0.3
UNET D2 Transverse Eddy Viscosity=0.1
UNET D2 Smagorinsky Mixing=0
UNET D2 BCVolumeCheck=0
UNET D2 Cores=0
UNET D2 SolverType=PARDISO (Direct)
UNET D2 Minimum Iterations= 3
UNET D2 Maximum Iterations= 30
UNET D2 Restart Number= 10
UNET D2 Relaxation Coeff=1.3
UNET D2 SOR Precondition Iterations= 10
UNET D2 ILUT Maximum Fill= 8
UNET D2 ILUT Tolerance=1E-08
UNET D2 Convergence Tolerance=0.00001
PS Theta= 1
PS WS Tol= 0.01
PS Volume Tol= 0.01
PS Max Iterations= 20
PS Equation= 0
PS Advance Time Step=-1
PS Target Courant=0.9
PS Time Slices= 1
PS Iterate With 2D=0
PS Project Initial WSE from DS=-1
PS Ramp Up Initial WSE from US=-1
PS Cores=0
UNET D1D2 MaxIter= 0
UNET D1D2 ZTol=0.01
UNET D1D2 QTol=0.1
UNET D1D2 MinQTol=1
Write IC File= 0
Write IC File at Fixed DateTime=0
Write IC File at Sim End=0
Echo Input=False
Echo Parameters=False
Echo Output=False
Write Detailed= 0
HDF Write Warmup=0
HDF Write Time Slices=0
HDF Flush=0
HDF Compression= 1
HDF Chunk Size= 1
HDF Spatial Parts= 1
HDF Use Max Rows=0
HDF Fixed Rows= 1
Calibration Method= 0
Calibration Iterations= 20
Calibration Max Change=0.05
Calibration Tolerance=0.2
Calibration Maximum=1.5
Calibration Minimum=0.5
Calibration Optimization Method= 1
WQ AD Non Conservative
WQ ULTIMATE=-1
WQ Max Comp Step=1HOUR
WQ Output Interval=15MIN
WQ Output Selected Increments= 0
WQ Create Restart=0
WQ Fixed Restart=0
WQ System Summary=0
WQ Write To DSS=0
Sorting and Armoring Iterations= 10
XS Update Threshold= 0.02
Bed Roughness Predictor= 0
Processes Affected by Predictor=Sediment Only
Hydraulics Update Threshold= 0.02
Energy Slope Method= 1
Volume Change Method= 1
Sediment Retention Method= 0
Sediment TS Multiplier= 1
Warm Up Method= 0
XS Weighting Method= 0
Number of US Weighted Cross Sections= 1
Number of DS Weighted Cross Sections= 1
Upstream XS Weight=0
Main XS Weight=1
Downstream XS Weight=0
Number of DS XS's Weighted with US Boundary= 1
Upstream Boundary Weight= 1
Weight of XSs Associated with US Boundary= 0
Number of US XS's Weighted with DS Boundary= 1
Downstream Boundary Weight= 0.5
Weight of XSs Associated with DS Boundary= 0.5
Percentile Method= 0
Sediment Output Level= 3
Mass or Volume Output= 0
Output Increment Type= 1
Profile and TS Output Increment= 1
Transport Output Increment 1
XS Output Flag= 0
XS Output Increment= 10
Read HDF5 Sediment Hotstart= 0
Sediment Hotstart Type= 0
Write Gradation File= 0
Read Gradation Hotstart= 0
Write HDF5 File= 1
Write Binary Output= 1
Write DSS Sediment File= 0
DSS Sediment Output Type= 1
SV Curve= 0
Specific Gage Flag= 0
Subcell Erosion Methods= 0
Subcell Deposition Methods= 0
Advection Scheme= 1
Matrix Solver= 0
Implicit Weighting Factor= 1
Maximum Outer Loop Convergence Iterations= 5
Convergence Maximum Absolute= 0.001
Convergence RMSE= 0.0001
Grain Fractions Max Abs Error= 0.001
Max Subgrid Regions= 1
Max Subgrid Length Scale= 3.402823E+38
Initial Layer Thickness= 3
Min Layer Thickness= 0.1
Max Layer Thickness= 6
Number of Layers= 5

--- BurchRnI.f01 (steady flow) ---

Flow Title=Flow
Program Version=6.60
Number of Profiles= 1
Profile Names=P100yr
River Rch & RM=BurchRnI,Main            ,15635
     801
River Rch & RM=BurchRnI,Main            ,11999
     988
River Rch & RM=BurchRnI,Main            ,11099
    1110
River Rch & RM=BurchRnI,Main            ,7432
    1240
River Rch & RM=BurchRnI,Main            ,4423
    1780
Boundary for River Rch & Prof#=BurchRnI,Main            , 1
Up Type= 0
Dn Type= 3
Dn Slope=0.005252
DSS Import GetInterval= 0
DSS Import GetPeak= 0
DSS Import FillOption= 0

--- BurchRnI.g01 (geometry) ---

Geom Title=Geometry
Program Version=6.60

River Reach=BurchRnI        ,Main
Reach XY= 30
     1648636.763      528212.954     1648756.474      528240.271
     1649200.376       528882.99     1649496.012      528946.034
      1649527.18      529251.166     1649825.016      529396.475
      1650136.66      529917.451     1650224.222      530274.465
     1650046.468      530803.074     1650280.365      531246.987
     1650605.621      531469.494      1650595.98      531600.543
     1651028.903       532288.47      1650945.13      532574.183
     1651186.011      532947.675     1651174.654      533230.403
     1651703.405      534104.312     1651816.209      534801.886
     1651700.645      535185.791      1652186.18      535505.712
     1652600.697      536026.471     1653057.898       536267.47
     1653552.659      536276.208     1653551.813      536407.121
     1653867.273      536589.974     1653644.249      537612.675
     1653318.034      537786.126     1652640.915      538386.335
      1652528.87      538744.523     1651741.744      539577.716

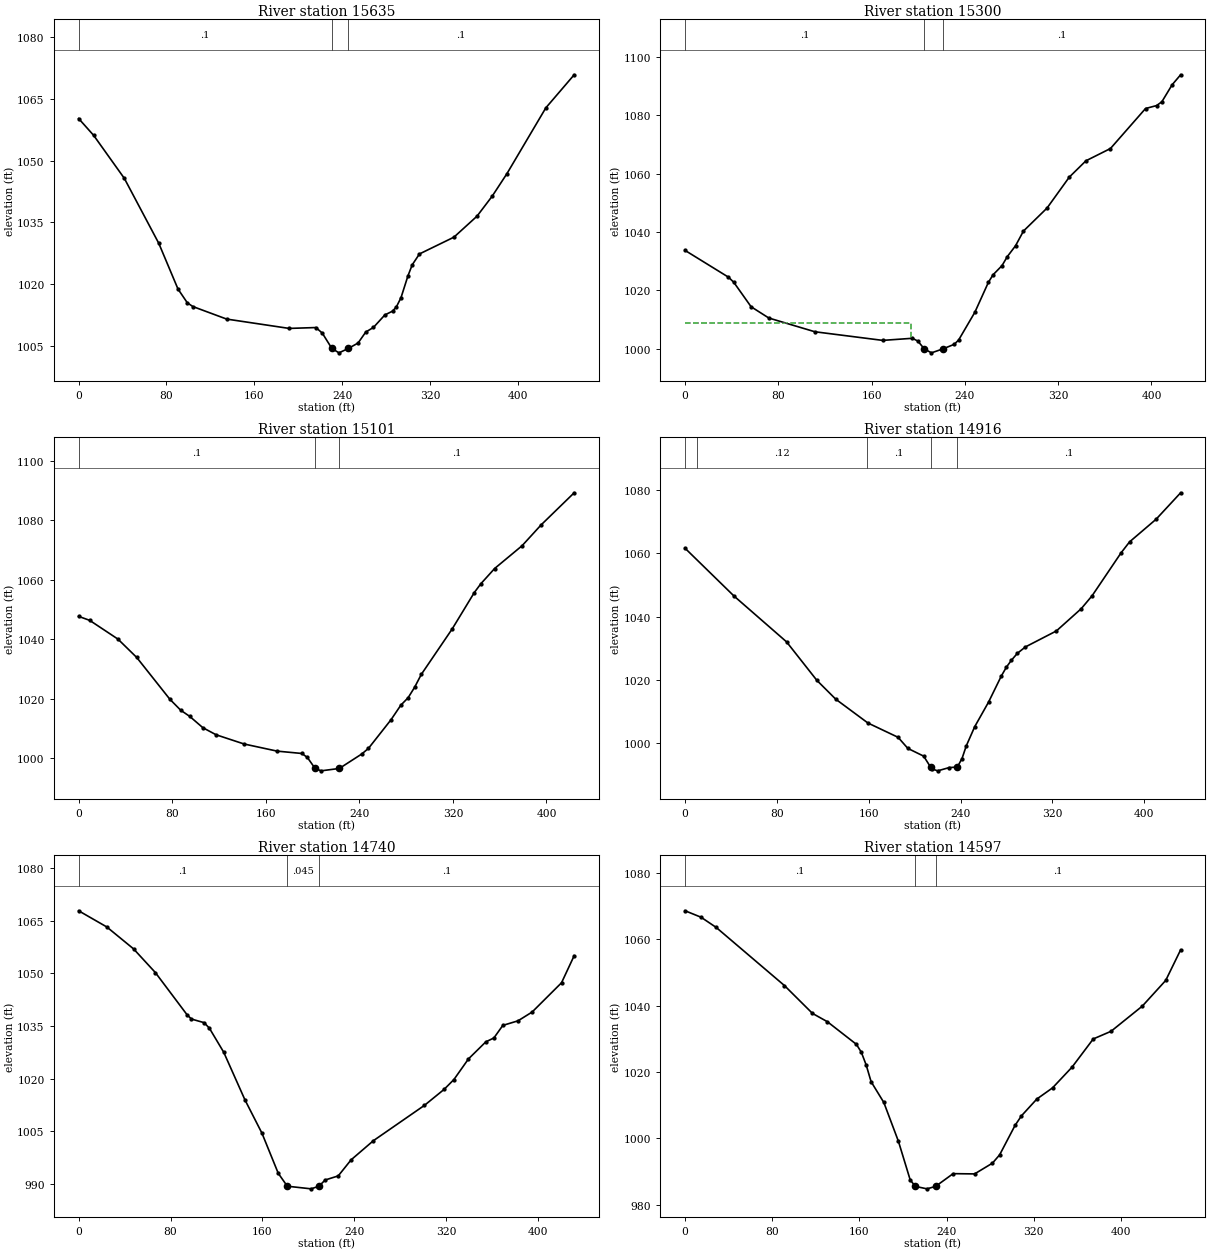
Type RM Length L Ch R = 1 ,15635   ,330.6,334.7,336.1
XS GIS Cut Line= 2
 1648576.2198221528444.5976305241648730.26211867528020.368797511
#Sta/Elev= 30
       0 1060.21    13.7 1056.11    41.6 1045.67      73 1029.86    90.5 1018.74
      99 1015.39   104.1 1014.48   134.8 1011.44   191.7 1009.17   216.1 1009.38
   221.9 1008.03  230.621004.298   237.1 1003.23  245.66  1004.3   254.5 1005.62
   261.5 1008.29   268.5 1009.41   278.9 1012.45   285.9 1013.37   289.4 1014.41
   293.6 1016.65   299.9 1021.94   303.8 1024.63   310.4 1027.28   341.8 1031.36
   362.8 1036.46   376.7 1041.35   390.1 1046.82   425.5 1062.81   451.3 1070.85
#Mann= 3, -1 ,  0
       0     0.1       0  230.62   0.045       0  245.66     0.1       0
Bank Sta=230.62,245.66
XS Rating Curve= 0 ,0
Exp/Cntr(USF)=0,0
Exp/Cntr=0.3,0.1

Type RM Length L Ch R = 1 ,15300   ,197.6,199.3,201.7
XS GIS Cut Line= 6
1648751.30669601528584.3486406651648808.99686934528518.560714498
1648858.44591743528462.1710635131648924.37754409528386.984206006
1648973.82659218528330.5945550051649032.34845676528265.535630003
#Sta/Elev= 30
       0  1033.7    37.2 1024.55    41.7 1022.83    56.6 1014.44    71.8 1010.58
   111.3 1005.88   169.5 1002.93     195 1003.65   199.7 1002.67  205.131000.021
   211.3  998.67  221.111000.018   230.8 1001.58   234.6 1003.06   248.5 1012.54
   260.1 1022.77   264.1 1025.36   271.8 1028.51   276.4 1031.62   283.4  1035.3
   290.2 1040.33   310.4 1048.19   329.5 1058.78   343.8 1064.37   364.8 1068.56
   394.9 1082.25   404.4 1083.26   408.9 1084.56   417.7 1090.37     425 1093.79
#Mann= 3, -1 ,  0
       0     0.1       0  205.13   0.045       0  221.11     0.1       0
#XS Ineff= 2 , 0
          193.86 1008.99
Permanent Ineff=
       F       F
Bank Sta=205.13,221.11
XS Rating Curve= 0 ,0
Exp/Cntr(USF)=0,0
Exp/Cntr=0.3,0.1

Type RM Length L Ch R = 1 ,15101   ,182.8,184.2,185.6
XS GIS Cut Line= 2
1648849.85213365528696.8017024111649194.99733679528451.130662621
#Sta/Elev= 30
       0 1047.67     9.4 1046.34    33.6 1040.04    49.7 1033.86      78 1019.84
    87.3 1016.15      95 1014.08   106.2 1010.29   117.6  1007.9   141.5 1004.81
   169.7 1002.42   190.9 1001.63   195.6 1000.28  202.19996.6035   207.3   995.8
  222.89996.5998   242.1 1001.46   247.8 1003.34   267.1 1012.96   275.5 1017.85
   281.7 1020.34   287.3 1023.87     293 1028.19   319.5 1043.51   338.3 1055.66
   343.9 1058.62   355.7 1063.74   379.1 1071.37   395.5 1078.41   423.7 1089.17
#Mann= 3, -1 ,  0
       0     0.1       0  202.19   0.045       0  222.89     0.1       0
Bank Sta=202.19,222.89
XS Rating Curve= 0 ,0
Exp/Cntr(USF)=0,0
Exp/Cntr=0.3,0.1

Type RM Length L Ch R = 1 ,14916   ,176.5,177,172.8
XS GIS Cut Line= 5
1648944.28409151528842.7505751341649015.90927634528790.983618313
 1649077.7644676528747.7113951381649170.41358319 528698.79945742
1649293.63246633528591.884629743
#Sta/Elev= 30
       0 1061.61    42.7 1046.47    88.4    1032   114.8 1019.82   131.3 1013.84
   159.3 1006.31   185.6 1001.78   194.1  998.27   207.9  995.82  213.89992.3569
   215.4  991.76   220.1  991.17   230.2  992.21  237.17992.3554   241.3  995.06
     245  999.06   252.4 1005.17   264.4 1012.91   275.6 1021.22     280    1024
   284.4  1026.2   289.6 1028.39   296.6  1030.4   323.5 1035.44   345.2  1042.5
   354.7 1046.61   379.9 1060.17   387.3 1063.64   410.4  1070.8   431.8 1079.18
#Mann= 5, -1 ,  0
       0     0.1       0      10    0.12       0  158.37     0.1       0
  213.89   0.045       0  237.17     0.1       0
Bank Sta=213.89,237.17
XS Rating Curve= 0 ,0
Exp/Cntr(USF)=0,0
Exp/Cntr=0.3,0.1

Type RM Length L Ch R = 1 ,14740   ,147.9,142.5,124
XS GIS Cut Line= 3
1649040.20933432528978.9140953071649238.70568129528853.548868903
1649364.17489284528702.111856595
#Sta/Elev= 30
       0 1067.86    24.5 1063.25    47.8    1057    66.8 1050.24    94.3 1038.24
    98.2 1036.98   109.2 1035.95   113.8 1034.39   126.3 1027.52   144.8 1013.92
   159.6 1004.42   173.8  992.97  181.67989.2991   202.4  988.55  209.22   989.3
   214.6  991.07     226  992.24   237.2  996.82   256.6 1002.28   301.1 1012.37
   318.1  1016.9   326.7 1019.72   339.4 1025.62   354.5 1030.48   361.5 1031.58
   369.3 1035.17   382.5 1036.47   394.8 1038.98   420.4 1047.33   431.4 1055.05
#Mann= 3, -1 ,  0
       0     0.1       0  181.67   0.045       0  209.22     0.1       0
Bank Sta=181.67,209.22
XS Rating Curve= 0 ,0
Exp/Cntr(USF)=0,0
Exp/Cntr=0.3,0.1

Type RM Length L Ch R = 1 ,14597   ,184,200.7,209.4
XS GIS Cut Line= 4
1649198.01170537529104.4950537191649322.35440956528971.109243772
1649322.35440956528846.7665395841649381.88818914528711.119953197
#Sta/Elev= 30
       0 1068.59    14.6 1066.65    28.5 1063.58    91.2 1046.04   116.9 1037.65
   130.6 1035.14   157.2 1028.33   161.7 1025.97   166.2  1022.1   170.7 1017.07
   182.4 1010.79   195.8  999.08   206.6  987.45  211.35 985.495     222  984.76
  229.89985.4954     246  989.34   265.7  989.26   282.1  992.51   288.7  995.02
   302.8 1003.87   308.7 1006.77   322.8 1011.83   337.2 1015.19   355.1 1021.44
   374.6 1029.95   390.9 1032.25   419.6 1039.84   441.1 1047.59   454.8 1056.81
#Mann= 3, -1 ,  0
       0     0.1       0  211.35   0.045       0  229.89     0.1       0
Bank Sta=211.35,229.89
XS Rating Curve= 0 ,0
Exp/Cntr(USF)=0,0
Exp/Cntr=0.3,0.1

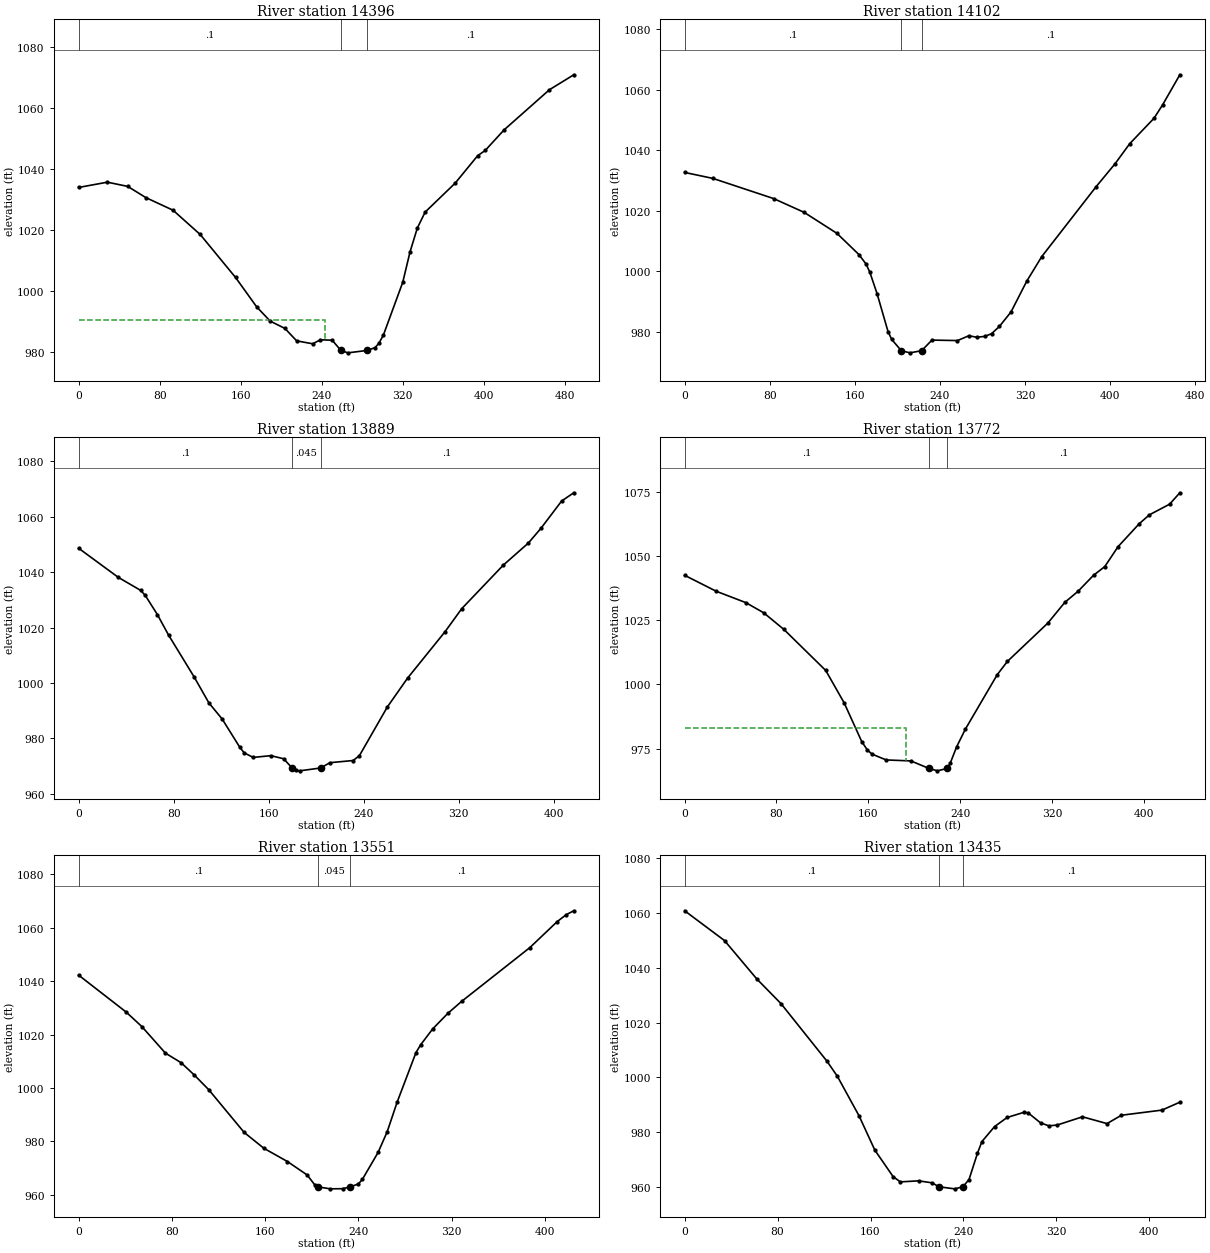
Type RM Length L Ch R = 1 ,14396   ,284.4,294.6,294
XS GIS Cut Line= 6
1649297.70422526529143.3051999211649386.01540034529061.365075082
1649459.68651284 528986.588321761649545.04395367528934.346628338
1649611.78299342528899.2938769161649688.94589683528857.387136593
#Sta/Elev= 30
       0 1033.91    28.4 1035.64    48.5 1034.25    66.4 1030.57    93.2 1026.44
     120 1018.48   154.9 1004.38   175.7  994.75   189.1  990.06   203.6  987.67
   215.2  983.59     231  982.63   238.7  983.94   250.3   983.8  258.84980.4453
   265.7  979.66  284.86980.4455   292.6  981.38   296.4   982.8   300.8  985.49
   319.9  1002.8   327.1 1012.79   334.3  1020.6     342 1025.83   371.6 1035.31
   393.8 1044.31   401.3 1046.05   419.9 1052.79   464.7 1065.97   488.7 1070.87
#Mann= 3, -1 ,  0
       0     0.1       0  258.84   0.045       0  284.86     0.1       0
#XS Ineff= 2 , 0
          243.32   990.5
Permanent Ineff=
       F       F
Bank Sta=258.84,284.86
XS Rating Curve= 0 ,0
Exp/Cntr(USF)=0,0
Exp/Cntr=0.3,0.1

Type RM Length L Ch R = 1 ,14102   ,222.4,212.6,200.6
XS GIS Cut Line= 6
 1649311.2212586 529291.771438421649394.81820425529265.965059593
1649466.53394009529244.0366257581649565.40218067529213.356240928
1649645.18581375529175.6912900061649741.34572643529119.482084841
#Sta/Elev= 30
       0 1032.69    26.5 1030.72    83.6 1024.05   112.3 1019.49   143.2 1012.53
   163.8 1005.53   170.6 1002.36   174.1  999.67   180.9   992.6   191.2  980.05
   194.7  977.42  203.72973.6984   211.8  972.99  222.81973.6975   232.5  977.21
   256.5  977.05   267.2  978.64   274.6  978.16     282  978.42   288.6  979.33
   295.9  981.72   306.8  986.49   321.6  996.67   335.8 1004.86     387 1028.03
   404.7 1035.57   418.5 1042.21   441.3 1050.61   449.4 1055.06   465.6 1065.01
#Mann= 3, -1 ,  0
       0     0.1       0  203.72   0.045       0  222.81     0.1       0
Bank Sta=203.72,222.81
XS Rating Curve= 0 ,0
Exp/Cntr(USF)=0,0
Exp/Cntr=0.3,0.1

Type RM Length L Ch R = 1 ,13889   ,112,117.6,121.3
XS GIS Cut Line= 5
1649597.52552493529502.6602702281649646.51197551 529425.14336489
1649683.16413318529357.4922534811649704.47352836529257.609385982
1649755.76374352529121.000904813
#Sta/Elev= 30
       0 1048.62    33.4 1038.11    52.1 1033.44      56 1031.66    66.3 1024.68
    75.8 1017.21    97.3 1002.12   109.6  992.83   120.8     987   135.7  976.76
   139.4  974.77   146.9  973.14   161.8  973.78   172.6  972.65  179.65969.3252
   182.6  968.45     186   968.3  203.62969.3279   211.5  971.24   230.9  972.02
   236.2   973.7   259.8  991.34   276.8 1001.74   308.4 1018.52   322.4 1026.81
   357.4 1042.53   378.5  1050.5     389 1055.77   406.5 1065.67   416.7 1068.63
#Mann= 3, -1 ,  0
       0     0.1       0  179.65   0.045       0  203.62     0.1       0
Bank Sta=179.65,203.62
XS Rating Curve= 0 ,0
Exp/Cntr(USF)=0,0
Exp/Cntr=0.3,0.1

Type RM Length L Ch R = 1 ,13772   ,213.7,220.7,227.1
XS GIS Cut Line= 3
1649663.72790467529551.7904628451649768.48258847529406.230573347
1649937.36258852529219.038284132
#Sta/Elev= 30
       0  1042.5    27.4 1036.31    53.3 1031.86    68.9 1027.89    86.5  1021.4
   122.9 1005.44     139  992.77   154.3  977.71   159.2  974.44   163.3  972.84
   175.5  970.59   197.1   970.2  212.84967.2802   220.2  966.34  228.72967.2793
   231.3  969.24   236.9  975.65   244.6  982.62   272.3 1003.78   281.1 1008.93
   316.4 1023.89   331.2 1031.96   342.8 1036.31   356.2 1042.51     366 1045.89
   377.6 1053.67     396 1062.58   404.8 1066.04   422.5 1070.21   431.4 1074.65
#Mann= 3, -1 ,  0
       0     0.1       0  212.84   0.045       0  228.72     0.1       0
#XS Ineff= 2 , 0
          193.05  982.99
Permanent Ineff=
       F       F
Bank Sta=212.84,228.72
XS Rating Curve= 0 ,0
Exp/Cntr(USF)=0,0
Exp/Cntr=0.3,0.1

Type RM Length L Ch R = 1 ,13551   ,117.1,115.4,111.6
XS GIS Cut Line= 3
1649703.83950066529604.8802390581649969.27140118529539.568919686
 1650096.5447415529457.511108168
#Sta/Elev= 30
       0 1042.25    40.7 1028.46    54.2 1023.02    74.5 1013.04      88 1009.45
    99.3 1004.83   111.6  999.38     142  983.38   158.9  977.44   179.2  972.46
   196.1  967.43   202.8  963.62  205.71962.9602   215.9  962.25   226.5   962.3
  232.76962.9605     240  964.08   243.4  965.77   256.9  975.86   264.7  983.59
   273.3  994.75   289.4 1013.24   293.4 1016.16   303.7 1022.09   316.8 1027.96
   328.5 1032.39   387.1 1052.55   410.5 1062.26   418.3 1064.88   424.8 1066.34
#Mann= 3, -1 ,  0
       0     0.1       0  205.71   0.045       0  232.76     0.1       0
Bank Sta=205.71,232.76
XS Rating Curve= 0 ,0
Exp/Cntr(USF)=0,0
Exp/Cntr=0.3,0.1

Type RM Length L Ch R = 1 ,13435   ,197.5,198.4,197.7
XS GIS Cut Line= 6
1649762.34789181529761.8128075751649839.85626698529719.793862745
1649906.25213156529683.6856672461649996.54591422529640.423286587
1650064.83055456529609.4853563311650144.49181256529573.391924575
#Sta/Elev= 30
       0 1060.74    34.3 1049.88      62 1035.94    82.9 1026.91   122.5 1005.92
   131.4 1000.45   150.1  986.02   163.7  973.51   179.5  963.81   185.7  961.92
   201.4  962.29   212.8  961.59  219.06960.1105   232.5  959.38  239.45960.1117
   244.8  962.77   252.1  972.37   255.9  976.61   266.8  982.07   277.6  985.39
     292  987.26   295.6  987.11   306.4  983.42   313.6  982.34   320.8  982.65
   342.5  985.64   363.6  983.16     376  986.21   410.9  988.08   426.3  990.96
#Mann= 3, -1 ,  0
       0     0.1       0  219.06   0.045       0  239.45     0.1       0
Bank Sta=219.06,239.45
XS Rating Curve= 0 ,0
Exp/Cntr(USF)=0,0
Exp/Cntr=0.3,0.1

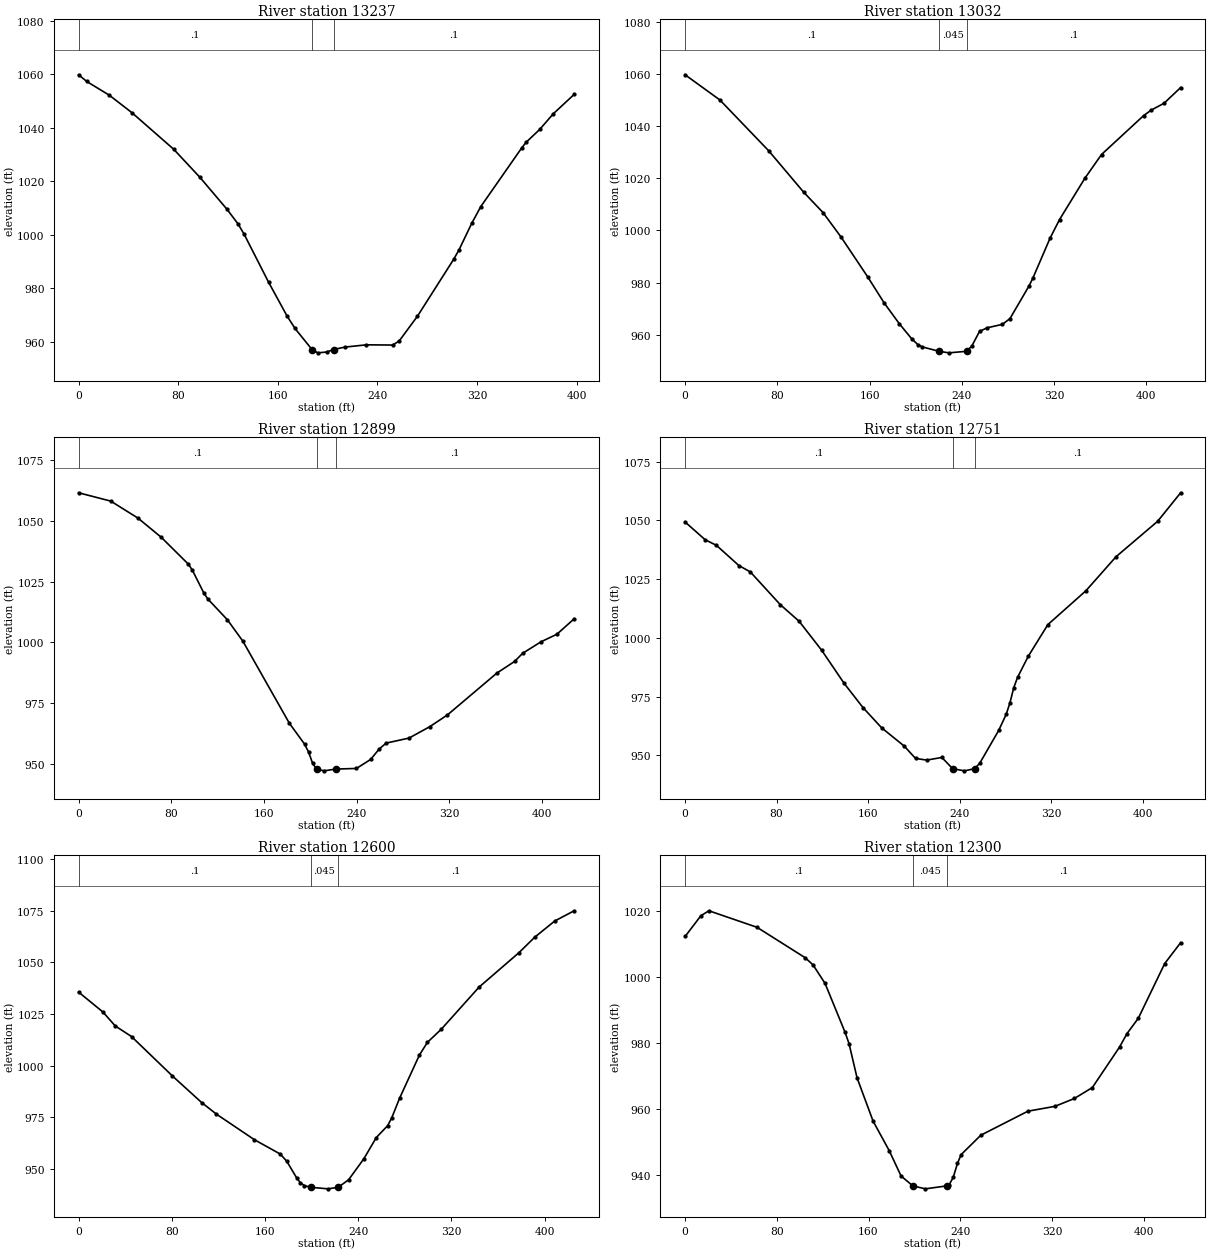
Type RM Length L Ch R = 1 ,13237   ,201.6,205.5,209.6
XS GIS Cut Line= 2
1649868.72973007529918.7677940771650227.60534281529746.678291156
#Sta/Elev= 30
       0 1059.88     6.5 1057.38    24.7 1052.22    42.9 1045.67    76.3 1032.05
    97.4 1021.53   119.3  1009.5     128 1004.12   132.9 1000.27   152.5  982.35
   167.3  969.73   173.8  964.99  187.42 957.127     192  955.88   199.2  956.18
  204.75957.1285   213.9  958.03   231.2  958.88   252.3  958.79   257.5  960.34
   272.1  969.56   301.2  990.85   305.4  994.29   315.7  1004.3     323 1010.58
   355.8 1032.48   359.4 1034.63   370.3 1039.43   381.2 1045.28     398 1052.55
#Mann= 3, -1 ,  0
       0     0.1       0  187.42   0.045       0  204.75     0.1       0
Bank Sta=187.42,204.75
XS Rating Curve= 0 ,0
Exp/Cntr(USF)=0,0
Exp/Cntr=0.3,0.1

Type RM Length L Ch R = 1 ,13032   ,133.1,133,132.2
XS GIS Cut Line= 2
1649910.22451036530026.4369981551650336.32969942529970.615357666
#Sta/Elev= 30
       0 1059.61    30.2 1049.95    72.6 1030.44     103 1014.54   119.6 1006.83
   135.2  997.47   158.6  982.02   172.5  972.28   185.7  964.27   196.6  958.41
     202  956.19   205.6  955.37  220.29953.6725   228.7  953.09  244.02953.6728
   248.6  955.67   255.3  961.29   261.8  962.67   275.1     964   281.7   966.2
   298.2  978.69   301.5  981.64   316.5  997.04   324.7 1004.15   346.7    1020
   361.1 1029.07   397.5 1043.93   404.1 1046.05   415.3  1048.7   429.7 1054.71
#Mann= 3, -1 ,  0
       0     0.1       0  220.29   0.045       0  244.02     0.1       0
Bank Sta=220.29,244.02
XS Rating Curve= 0 ,0
Exp/Cntr(USF)=0,0
Exp/Cntr=0.3,0.1

Type RM Length L Ch R = 1 ,12899   ,146.4,147.9,148.3
XS GIS Cut Line= 6
1649945.96277125530171.4471725081650031.73589367530152.793010339
1650105.49460442530136.9892361761650204.23620485530117.910534173
1650276.08678292530095.5746208431650358.96391375530063.480853006
#Sta/Elev= 30
       0 1061.52    27.7  1058.1    51.2 1051.12    71.3 1043.24    94.8 1032.15
    98.2 1029.71   108.2 1020.22   111.6 1017.83   128.4 1009.34   141.8 1000.52
     182  966.74   195.1  958.19   198.7  954.78     202  950.34   205.4  947.93
   211.9   947.2   222.1  947.93   239.9  948.18   252.1  951.87   259.5  956.15
   265.5   958.6   285.3  960.67   303.3  965.38   318.5   970.2   361.2  987.41
   376.4  992.16   383.4  995.52   399.3 1000.26     413 1003.37   427.9 1009.71
#Mann= 3, -1 ,  0
       0     0.1       0   205.4   0.045       0   222.1     0.1       0
Bank Sta=205.4,222.1
XS Rating Curve= 0 ,0
Exp/Cntr(USF)=0,0
Exp/Cntr=0.3,0.1

Type RM Length L Ch R = 1 ,12751   ,146.4,150.7,154.1
XS GIS Cut Line= 3
1649978.41994782530249.8258997831650199.97603892530259.622597689
1650409.47465567530230.232503972
#Sta/Elev= 30
       0 1049.35    17.6 1041.78    27.4 1039.42    47.1 1030.78      57 1028.12
    83.2 1014.18    99.7 1007.08   119.4  994.76   139.1  980.62   155.5  970.35
   171.9  961.69   191.6  953.93   201.5  948.67   211.3  947.97   224.5  949.09
  233.97944.3059   244.3  943.39  253.11944.3049   257.6   946.6   274.2  960.59
   280.8  967.47   284.1  972.45   287.4  978.82   290.7   983.2   300.1  992.21
   317.2 1005.66   350.4 1020.04   376.9 1034.61   413.2 1049.66   433.3  1061.8
#Mann= 3, -1 ,  0
       0     0.1       0  233.97   0.045       0  253.11     0.1       0
Bank Sta=233.97,253.11
XS Rating Curve= 0 ,0
Exp/Cntr(USF)=0,0
Exp/Cntr=0.3,0.1

Type RM Length L Ch R = 1 ,12600   ,298.9,300,300.1
XS GIS Cut Line= 6
1649976.40824842530331.4566950051650058.66858259 530362.24830009
1650130.44140492530384.0461567491650226.58163258530411.560209334
1650298.68680334 530432.195666761650382.80999467530456.270421758
#Sta/Elev= 30
       0 1035.62    20.9 1025.99    31.4 1019.27    45.4 1014.13    80.4  995.11
   105.6  982.19   118.3  976.58   150.8  964.24   173.1  957.26   178.6  953.82
   187.1  945.78   190.2  943.48   193.6  942.05  199.11941.2015   214.1  940.45
  222.78941.2021   231.7  944.84   244.8     955   255.5  965.28   265.2  971.01
   268.7  974.75   275.5  984.34   292.5 1005.21   299.4 1011.36   311.3  1017.7
   343.7 1038.06   377.9  1054.7   391.5 1062.22   408.6 1070.02   425.3 1074.98
#Mann= 3, -1 ,  0
       0     0.1       0  199.11   0.045       0  222.78     0.1       0
Bank Sta=199.11,222.78
XS Rating Curve= 0 ,0
Exp/Cntr(USF)=0,0
Exp/Cntr=0.3,0.1

Type RM Length L Ch R = 1 ,12300   ,310.5,300.7,288
XS GIS Cut Line= 6
1649855.06793992530597.2452054171649937.24100393530627.308465511
1650007.67557435530653.0771147611650101.58811617 530687.43432951
1650174.68311433530705.9296993321650269.11960526 530706.71545893
#Sta/Elev= 30
       0 1012.18    13.8 1018.47    20.8 1019.96    62.7 1014.97   104.6 1005.79
   111.6  1003.6   122.1  997.98   139.5  983.24     143  979.78     150  969.42
     164  956.31     178  947.42   188.4  939.71   198.7936.7073   209.6  935.82
  228.22936.7087   230.4   937.1   233.9  939.27   237.6  943.51   240.8  946.18
     258  952.05   299.1  959.32   322.6  960.78   339.6  963.16   355.3  966.48
     379  978.72   385.5  982.79   395.4  987.45   418.4 1003.99   432.3 1010.31
#Mann= 3, -1 ,  0
       0     0.1       0   198.7   0.045       0  228.22     0.1       0
Bank Sta=198.7,228.22
XS Rating Curve= 0 ,0
Exp/Cntr(USF)=0,0
Exp/Cntr=0.3,0.1

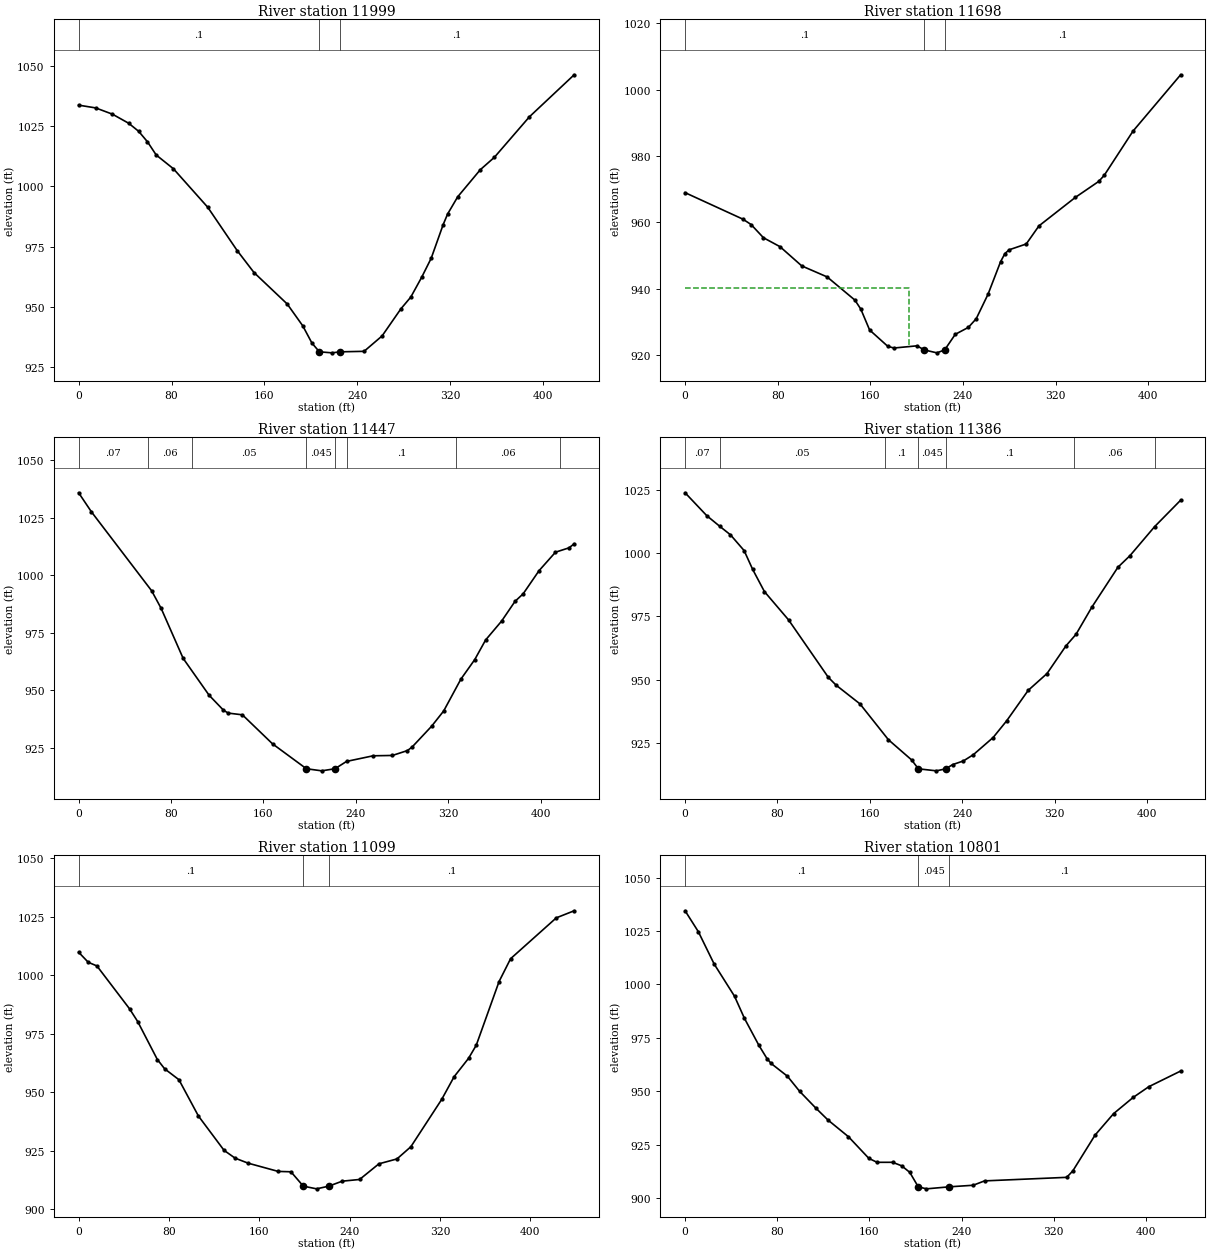
Type RM Length L Ch R = 1 ,11999   ,300.2,301.5,301.8
XS GIS Cut Line= 6
1649957.59004459531024.2879865021650034.86023125530980.223113999
1650103.08647275530948.4213403461650195.56266576530910.337755084
1650265.32696192530882.8072983321650346.71885951530850.688596174
#Sta/Elev= 30
       0 1033.74    14.7 1032.59    29.1 1029.99    43.1 1026.22    51.7 1022.87
    59.3 1018.51    66.8 1013.04    81.6 1007.33   111.2  991.32   136.5  973.36
     151  964.23   179.6  951.17     193  942.09   200.9  934.93  207.31 931.306
   218.1  930.88   225.3   931.3   245.8  931.51   261.3   937.9   277.5  949.16
     286  954.02   295.4  962.27   303.6  970.17   313.9  984.13   317.7  988.51
   326.4  995.67   345.9 1006.94     358 1012.08   388.2 1028.92   426.7 1046.35
#Mann= 3, -1 ,  0
       0     0.1       0  207.31   0.045       0   225.3     0.1       0
Bank Sta=207.31,225.3
XS Rating Curve= 0 ,0
Exp/Cntr(USF)=0,0
Exp/Cntr=0.3,0.1

Type RM Length L Ch R = 1 ,11698   ,251.9,250.7,246.6
XS GIS Cut Line= 6
1650058.26175925531280.035506502    1650139.4614531245.659591004
1650210.13645551531219.1665337531650306.36821842531191.342114344
1650373.79787359   531157.0810281650448.82725109531109.932828337
#Sta/Elev= 30
       0  968.96    49.9  960.99      57  959.37    67.7  955.39      82   952.7
   100.8  946.91   122.7   943.6   146.7  936.62   151.8  933.91   159.4  927.63
   175.1  922.71   180.4   922.2   200.3  922.86   206.7 921.618   217.5  920.75
  224.22921.6194   233.4  926.32   244.7  928.41   251.5  931.01   261.7  938.38
   272.6  948.22   276.3  950.63     280  951.77   294.7  953.51   305.7  958.96
   337.2  967.55   357.4  972.36   362.1  974.18   386.9  987.46   428.1 1004.44
#Mann= 3, -1 ,  0
       0     0.1       0   206.7   0.045       0  224.22     0.1       0
#XS Ineff= 2 , 0
          193.33  940.18
Permanent Ineff=
       F       F
Bank Sta=206.7,224.22
XS Rating Curve= 0 ,0
Exp/Cntr(USF)=0,0
Exp/Cntr=0.3,0.1

Type RM Length L Ch R = 1 ,11447   ,60.4,60.6,60.1
XS GIS Cut Line= 5
1650302.06550292 531529.049249371650356.65496067531460.351880211
1650402.00821642531400.6187319641650484.33274018531336.799313197
1650610.01497942531234.333401965
#Sta/Elev= 30
       0 1035.94    11.1 1027.64    63.2  993.34    71.5  985.63    90.5  963.94
     113  947.89   125.4  941.41   129.5  940.14   141.8  939.39   167.9  926.77
  197.22915.9435   210.5  915.03  221.98 915.942     232  919.13     255  921.57
   271.7  921.72   284.7  923.84   288.7  925.35   305.6   934.4   316.1  941.06
     331   954.9     343   963.4   352.4  971.92   366.3  980.17   377.9  988.74
   384.9  991.99   398.7 1002.08   412.9  1010.1   424.6 1011.99   429.1 1013.74
#Mann= 8, -1 ,  0
       0    0.07       0      60    0.06       0   97.75    0.05       0
  197.22   0.045       0  221.98    0.05       0  232.75     0.1       0
  326.91    0.06       0  416.91     0.1       0
Bank Sta=197.22,221.98
XS Rating Curve= 0 ,0
Exp/Cntr(USF)=0,0
Exp/Cntr=0.3,0.1

Type RM Length L Ch R = 1 ,11386   ,276.6,287.4,284.2
XS GIS Cut Line= 5
1650348.02988051 531566.167808251650402.61933826531497.470439091
1650447.97259401531437.7372908441650530.29711776531373.917872077
  1650655.979357531271.451960845
#Sta/Elev= 30
       0 1023.82    18.8 1014.77      30 1010.59    39.3 1007.22    51.1 1001.01
    58.5  993.59    68.7  984.81    89.6  973.64     124  950.98   130.8  947.86
   151.4   940.5   176.1  926.32   196.2  918.35  201.97914.8593   217.6  914.06
  225.76914.8587   231.6  916.51     241  917.97   249.7  920.47   266.7   927.2
   278.4  933.77   297.1  945.83   313.4  952.47   329.7  963.33   338.5  967.94
   352.1  978.59   374.8  994.43   385.2  998.98   406.6 1010.47   429.1 1020.89
#Mann= 7, -1 ,  0
       0    0.07       0      30    0.05       0  172.75     0.1       0
  201.97   0.045       0  225.76     0.1       0  336.91    0.06       0
  406.91     0.1       0
Bank Sta=201.97,225.76
XS Rating Curve= 0 ,0
Exp/Cntr(USF)=0,0
Exp/Cntr=0.3,0.1

Type RM Length L Ch R = 1 ,11099   ,296.3,297.7,299.5
XS GIS Cut Line= 6
1650418.43820426531717.8728854211650493.48956335531672.898894012
1650557.81817484531634.3468057511650644.52863134531584.466656178
1650722.57145426531562.7839567511650815.06175484531539.845026255
#Sta/Elev= 30
       0 1009.78     8.5 1005.49    16.2 1003.92    45.1  985.61    52.3  980.19
    69.7  963.98    76.2  959.99    88.8  955.36   106.1  939.84   128.8  925.19
   138.6  921.86     150  919.74   176.7  916.21     188  916.05  198.97909.9129
   210.7  908.77  221.46 909.912   233.4  912.04   248.8  912.77   265.9  919.45
   281.9  921.54   294.2  926.75   321.5  946.95   332.5  956.64   345.3   964.5
   352.1  970.08   372.3  997.27   382.5 1007.01     423 1024.46   438.8 1027.47
#Mann= 3, -1 ,  0
       0     0.1       0  198.97   0.045       0  221.46     0.1       0
Bank Sta=198.97,221.46
XS Rating Curve= 0 ,0
Exp/Cntr(USF)=0,0
Exp/Cntr=0.3,0.1

Type RM Length L Ch R = 1 ,10801   ,300.3,304.5,301.1
XS GIS Cut Line= 6
1650549.99338734531946.4524807481650631.23567893531913.956810832
1650700.87169451531886.1035200951650792.70320375531846.423481345
1650858.84119484531806.5570912511650932.56644109531754.386263832
#Sta/Elev= 30
       0 1034.47    11.5 1024.67    25.2 1009.57    42.9  994.48    51.5  984.14
    64.1  971.45    71.1  965.28    74.7     963    88.8  957.05    99.4  949.98
   113.5  942.11   124.1  936.51   141.8  928.72   159.5   918.6   166.6  916.75
   180.1  916.76     188  915.11     195  912.06  202.36 905.283   209.5  904.34
  229.32905.2817     250  906.01   259.9  908.06   331.2  909.72   336.5  912.72
   355.8  929.47   371.9  939.53   388.9  947.12   402.5  952.15   430.1  959.47
#Mann= 3, -1 ,  0
       0     0.1       0  202.36   0.045       0  229.32     0.1       0
Bank Sta=202.36,229.32
XS Rating Curve= 0 ,0
Exp/Cntr(USF)=0,0
Exp/Cntr=0.3,0.1

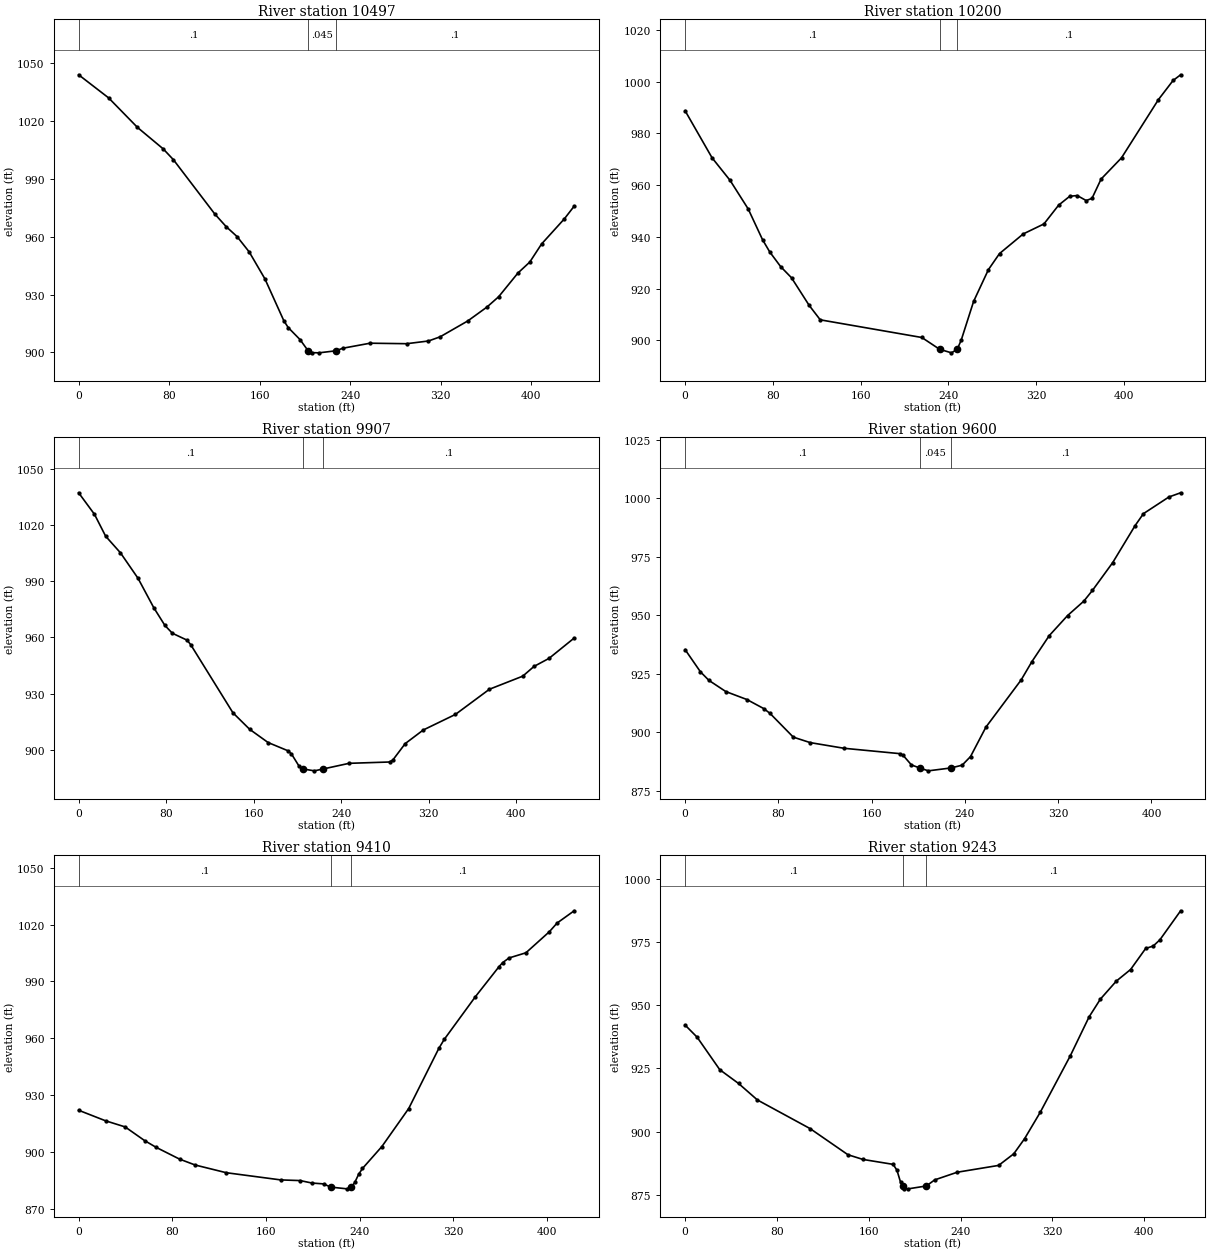
Type RM Length L Ch R = 1 ,10497   ,292.3,296.7,298.1
XS GIS Cut Line= 6
1650679.13387708532183.9795647561650760.68423893532152.265061259
1650830.58436158532125.0813885931650927.43751433532094.206450343
1651003.57253267532070.3482303321651092.96605468 532041.77479668
#Sta/Elev= 30
       0 1044.05    26.5 1032.06      52 1016.73    74.7 1005.61    83.7 1000.01
   120.3  971.81   130.4  965.22     140  960.09   150.7  952.14   164.6  938.14
   181.3  916.42   185.2  912.87   195.6  906.66  202.77900.8382   205.9  899.89
   212.3  899.78  227.28 900.838   233.4  902.17   257.5  904.78   289.8  904.52
   309.1  905.93   319.4   908.1   343.8  916.33   360.7  923.51   371.1   928.9
   388.1  941.18   398.6  946.89     409  956.26   429.1  969.28   437.8  975.88
#Mann= 3, -1 ,  0
       0     0.1       0  202.77   0.045       0  227.28     0.1       0
Bank Sta=202.77,227.28
XS Rating Curve= 0 ,0
Exp/Cntr(USF)=0,0
Exp/Cntr=0.3,0.1

Type RM Length L Ch R = 1 ,10200   ,297.2,292.9,286.1
XS GIS Cut Line= 6
1650781.79640143532343.7118568421650884.54094659532336.071780249
1650969.98434526532336.5471730081651068.10718051532359.767270923
1651141.10440984532376.8266200131651226.26532875532396.730779678
#Sta/Elev= 30
       0  988.78    24.6  970.57      41  961.86    57.5  950.83    70.6  938.92
    77.2  934.17    87.1  928.52      97  924.21   113.1  913.53   123.2  907.95
   215.8  901.12  231.95896.5732   242.8  895.19  248.06896.5707   251.7  900.11
     263  915.09   276.5  927.37   286.6  933.56   308.2  941.15   327.1  945.02
   340.5  952.29   350.6  955.71   357.4     956   365.6  954.06   370.9   954.9
   379.2  962.37   397.8  970.57   431.5  993.11   444.8 1000.47   451.7 1002.68
#Mann= 3, -1 ,  0
       0     0.1       0  231.95   0.045       0  248.06     0.1       0
Bank Sta=231.95,248.06
XS Rating Curve= 0 ,0
Exp/Cntr(USF)=0,0
Exp/Cntr=0.3,0.1

Type RM Length L Ch R = 1 ,9907    ,305.7,307.3,305.7
XS GIS Cut Line= 6
1650756.23903784532676.8532509211650841.09352693532654.610841334
1650914.42736976532637.5377127531651008.82547492532602.722821757
1651083.47722851532560.5244153441651182.65813251532530.161943257
#Sta/Elev= 30
       0 1037.12    14.5 1025.62    24.7 1013.95    38.2 1005.11    54.3  991.49
    68.7   975.8    78.9  966.31    85.7  962.16    99.2  958.45   102.5  956.04
   141.1   919.7   156.4  910.89   173.2  903.85   191.2  899.49   194.6  897.77
   201.6  891.17  204.99889.7431   215.6  888.73   223.7889.7429   247.3  892.74
   284.3  893.45   287.3  894.51   298.6  903.26   315.1  910.52   344.5  918.83
   375.6  932.27   406.1  939.26   416.4  944.46   430.1  948.74   453.1  959.59
#Mann= 3, -1 ,  0
       0     0.1       0  204.99   0.045       0   223.7     0.1       0
Bank Sta=204.99,223.7
XS Rating Curve= 0 ,0
Exp/Cntr(USF)=0,0
Exp/Cntr=0.3,0.1

Type RM Length L Ch R = 1 ,9600    ,187.8,190.3,193.1
XS GIS Cut Line= 6
1650941.94995251532945.4793540841651021.29001692532908.582118168
1651089.29578643   532876.9555411651179.97014576532834.787318259
1651247.97591525 532803.161069171651327.31597967532766.263833255
#Sta/Elev= 30
       0  935.24    13.2  925.72    20.5  922.07    34.9  917.32      53  913.91
    67.5  910.03    72.8     908    92.8  897.84   107.3   895.5   136.3  893.08
   183.9   890.8   186.9  890.11   194.1  885.97  201.13884.6818   208.6  883.44
  228.12884.6821   237.6  885.86   244.8  889.54     258  902.12   288.2  922.27
   297.5  930.15   312.3  941.21     328  949.77     342  955.97   349.4  960.56
   366.7  972.39   385.9  988.19   393.1  993.33   414.9 1000.44     425 1002.25
#Mann= 3, -1 ,  0
       0     0.1       0  201.13   0.045       0  228.12     0.1       0
Bank Sta=201.13,228.12
XS Rating Curve= 0 ,0
Exp/Cntr(USF)=0,0
Exp/Cntr=0.3,0.1

Type RM Length L Ch R = 1 ,9410    ,163.3,166.4,163.8
XS GIS Cut Line= 2
1650983.70831074533066.3953271871651401.44025373532998.478997926
#Sta/Elev= 30
       0   922.2      23  916.65    39.7  913.43    56.3  906.24    66.2  902.67
    86.2  896.47    99.5  893.37   126.1  889.31   172.6  885.52   189.2  885.17
   199.2  883.88   209.2  883.42  215.15881.7548   229.1  880.82  232.94 881.754
   235.8  884.16   239.1  888.42   242.4  891.54     259  903.11   281.9  923.12
   307.6  954.75   312.2  959.48   338.8  981.96   358.7  997.55   362.1  999.93
   367.6 1002.39     382 1005.11     402 1016.19   408.6 1020.76   423.2 1027.23
#Mann= 3, -1 ,  0
       0     0.1       0  215.15   0.045       0  232.94     0.1       0
Bank Sta=215.15,232.94
XS Rating Curve= 0 ,0
Exp/Cntr(USF)=0,0
Exp/Cntr=0.3,0.1

Type RM Length L Ch R = 1 ,9243    ,113.7,113,108
XS GIS Cut Line= 2
1650976.27560725533192.0907592111651407.62388992533172.454950005
#Sta/Elev= 30
       0  942.11    10.5   937.3    30.2  924.46    46.6     919      63  912.48
     109  901.13   141.9  890.81     155  888.95   181.3     887   184.6  884.68
   187.8  879.86  189.65878.4528   191.1  877.35   194.4  877.32  210.22878.4545
   217.5  880.86   237.1  883.89   273.2  886.59   286.4  891.18   295.8  897.14
   309.4  907.55   335.6   929.9     352  945.32   361.9  952.39   375.8  959.52
   388.2  964.09   401.3   972.4   407.9  973.38   413.7  975.82   431.8  987.32
#Mann= 3, -1 ,  0
       0     0.1       0  189.65   0.045       0  210.22     0.1       0
Bank Sta=189.65,210.22
XS Rating Curve= 0 ,0
Exp/Cntr(USF)=0,0
Exp/Cntr=0.3,0.1