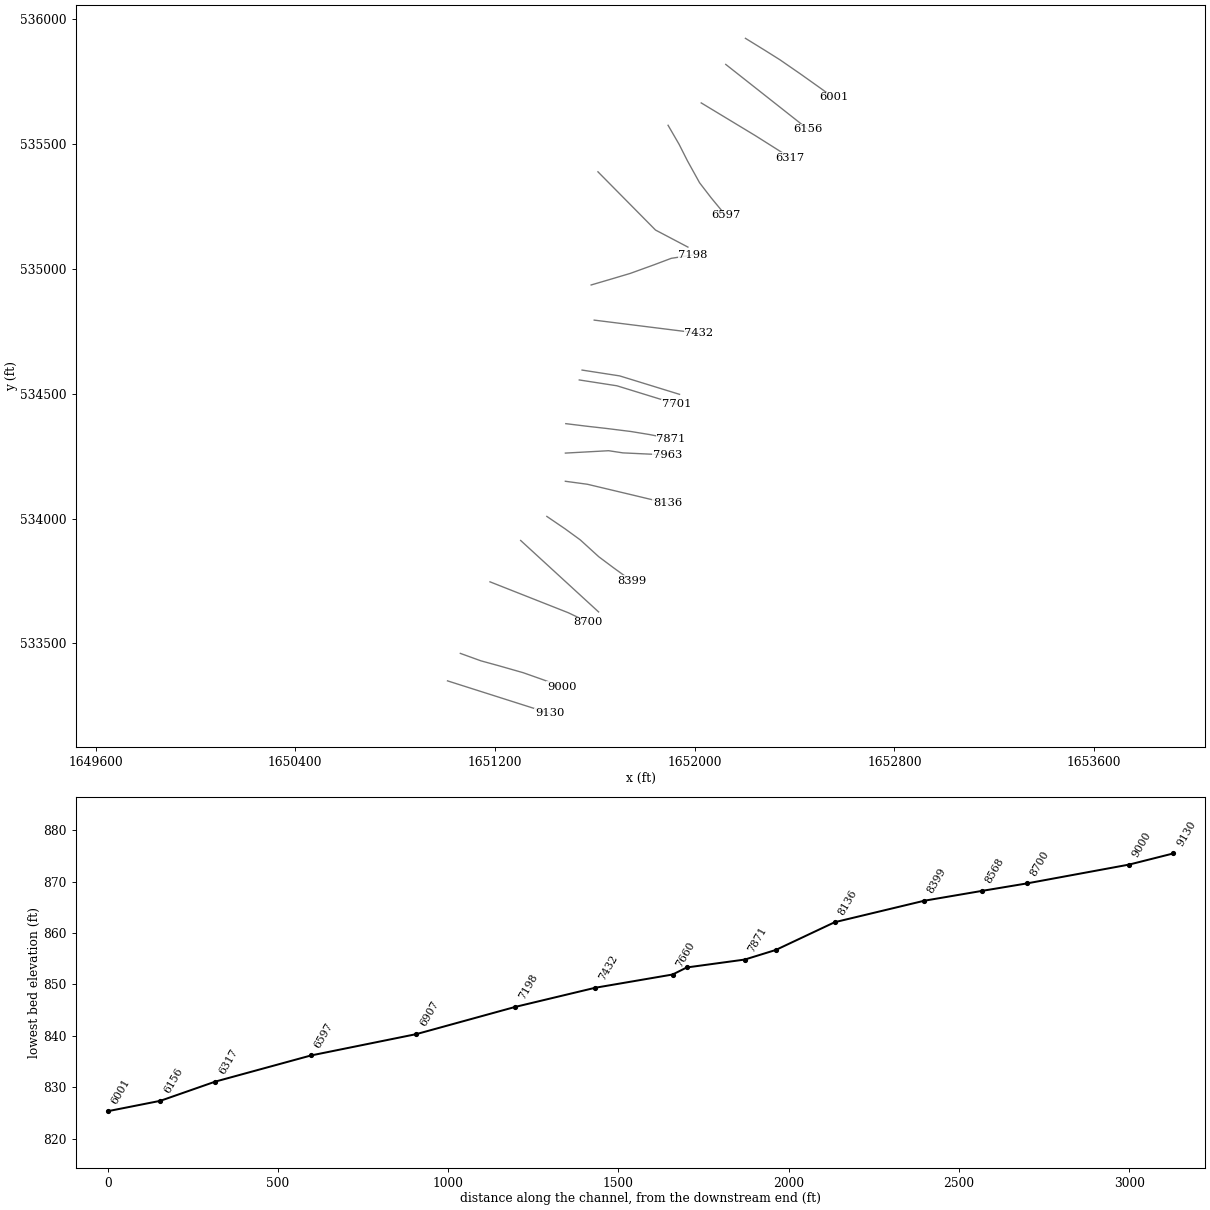
HEC-RAS study BurchRnI.prj: BurchRnI

--- BurchRnI.g01 (geometry) --- (continued)

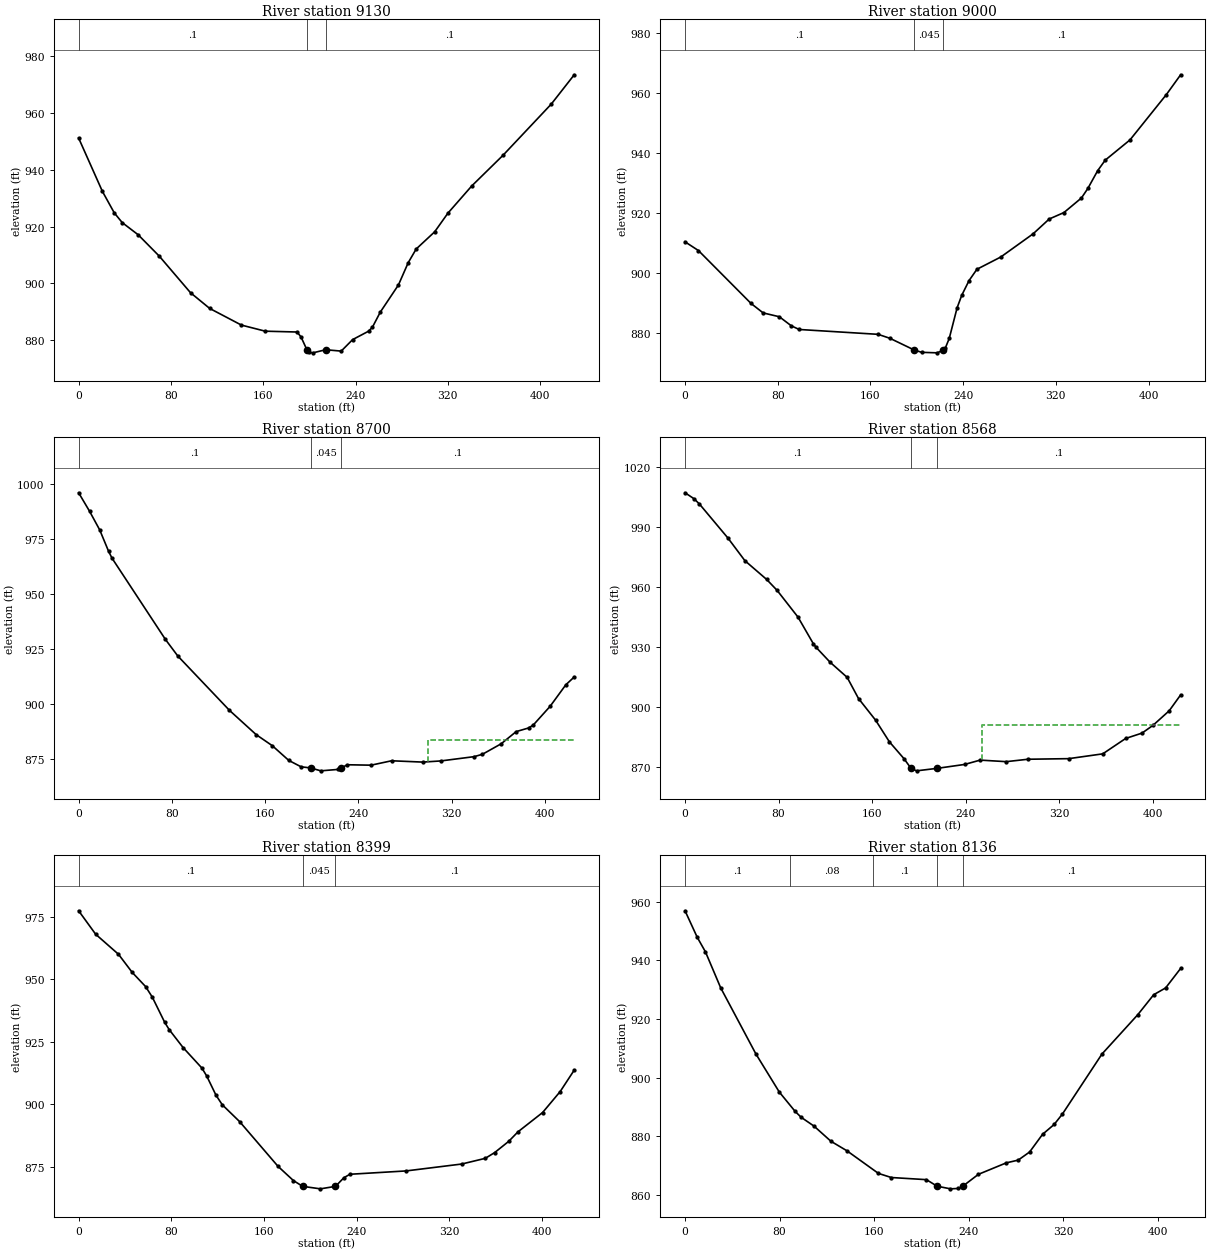
Type RM Length L Ch R = 1 ,9130    ,126.5,129.8,128.8
XS GIS Cut Line= 2
1651009.75840963533350.1553330041651419.11710655 533219.90483853
#Sta/Elev= 30
       0  951.18    20.6  932.39    30.9  924.81    37.8  921.38    51.6   917.1
    69.9  909.57      97  896.67   113.6  891.14   141.1  885.27   161.8  883.12
   189.3  882.83   192.8  881.08  197.84876.5879   199.6  875.66   203.1  875.49
  214.17 876.586   227.6   876.1   237.5  880.15   251.3  883.11   254.7  884.55
   261.5  889.85   277.2   899.4   285.7  907.27   292.6  912.08   308.6  918.13
   320.1  924.71   340.8  934.32   367.8  945.08   409.7  963.15   429.6  973.48
#Mann= 3, -1 ,  0
       0     0.1       0  197.84   0.045       0  214.17     0.1       0
Bank Sta=197.84,214.17
XS Rating Curve= 0 ,0
Exp/Cntr(USF)=0,0
Exp/Cntr=0.3,0.1

Type RM Length L Ch R = 1 ,9000    ,300.4,300.5,298.2
XS GIS Cut Line= 6
1651061.14754875533460.1840333341651143.62540217533430.360930249
1651215.94087434533410.475471333 1651313.0515725533382.762272179
 1651384.6144215533357.5208528341651467.44791725533327.472356498
#Sta/Elev= 30
       0  910.33    11.6  907.41      57  889.77    67.4  886.63    81.4  885.35
    91.7  882.33    98.5  881.11   166.6  879.49   176.8  878.17  197.97874.2313
   204.3  873.49   217.6  873.32   222.9  874.23   224.6   874.9     228  878.11
   234.8  888.34   238.8   892.5   245.1  897.41   251.9  901.18   272.5  905.27
   300.4     913   314.3  917.94     327  920.09   342.1  924.95   347.6  928.11
   356.1  934.05   362.6  937.55     384  944.31   415.4  959.43   427.7  966.02
#Mann= 3, -1 ,  0
       0     0.1       0  197.97   0.045       0   222.9     0.1       0
Bank Sta=197.97,222.9
XS Rating Curve= 0 ,0
Exp/Cntr(USF)=0,0
Exp/Cntr=0.3,0.1

Type RM Length L Ch R = 1 ,8700    ,135.5,131.5,126.2
XS GIS Cut Line= 6
  1651179.923886533746.7976333351651261.31217468533714.670072928
1651331.07417426533687.132726416 1651424.0890801533650.415280178
1651493.85107967 533622.878261761651573.03432025533585.164426416
#Sta/Elev= 30
       0  995.91     9.4   987.5    18.1  979.03    25.7  969.34    28.6  966.25
    74.5  929.29    85.1  921.78   129.4  897.12   152.3   886.1   166.2  881.05
   180.3  874.38   190.9  871.47  198.95870.9802   207.8  869.65   222.6   870.3
  225.25870.9794   230.6  872.41   250.9  872.22   268.5  874.22   295.3  873.62
   310.8  874.15   339.3  876.09   346.4  877.16   362.5  881.93   375.4  887.47
     386  889.11     390  890.42   404.5  898.94     418  908.73   425.2  912.27
#Mann= 3, -1 ,  0
       0     0.1       0  198.95   0.045       0  225.25     0.1       0
#XS Ineff= 2 , 0
                             300          883.46
Permanent Ineff=
       F       F
Bank Sta=198.95,225.25
XS Rating Curve= 0 ,0
Exp/Cntr(USF)=0,0
Exp/Cntr=0.3,0.1

Type RM Length L Ch R = 1 ,8568    ,167,169.9,167.8
XS GIS Cut Line= 2
1651302.72439176533912.4848509471651615.04647029 533626.11983524
#Sta/Elev= 30
       0  1006.9     7.5    1004    12.2 1001.37    36.7   984.3    51.2  973.01
    69.8  963.66    78.7  958.23    96.6  944.86   109.7  931.59     112  929.83
     124  922.39   138.6  914.83   148.3  904.28   162.9  893.48   174.7  882.68
   187.2  874.26  193.18869.4612   197.9   868.2  215.82869.4615     239  871.39
   252.3  873.55   274.6  872.78   293.1  873.98     328  874.28   357.1  876.67
   376.7  884.35   390.7  887.03     400  890.86   413.9  898.14   423.7  906.08
#Mann= 3, -1 ,  0
       0     0.1       0  193.18   0.045       0  215.82     0.1       0
#XS Ineff= 2 , 0
                          253.82          890.86
Permanent Ineff=
       F       F
Bank Sta=193.18,215.82
XS Rating Curve= 0 ,0
Exp/Cntr(USF)=0,0
Exp/Cntr=0.3,0.1

Type RM Length L Ch R = 1 ,8399    ,252.1,263,265.9
XS GIS Cut Line= 6
1651407.65276125534008.8017024991651480.67590918533959.077064425
1651541.66102342533914.6552372571651615.68318509533847.257078096
1651676.35793251 533801.908743591651747.84269768533750.387193084
#Sta/Elev= 30
       0  977.33    14.7  967.96    34.4  959.96    46.3  952.69    57.8  947.06
    63.6  942.84    74.3  932.77    78.2  929.85    90.2  922.68   106.4  914.52
   110.5  911.39   118.6  903.65     124  899.85   138.9  893.16   172.1  875.27
   185.4  869.58  193.41867.2679   208.7  866.28  221.72867.2684     229  870.73
   234.2   872.1   282.6  873.43   330.7  876.19     351  878.46   359.1  880.75
   371.2  885.23   379.3  889.07   400.5  896.76   415.7  905.15   427.8   913.7
#Mann= 3, -1 ,  0
       0     0.1       0  193.41   0.045       0  221.72     0.1       0
Bank Sta=193.41,221.72
XS Rating Curve= 0 ,0
Exp/Cntr(USF)=0,0
Exp/Cntr=0.3,0.1

Type RM Length L Ch R = 1 ,8136    ,168.4,172.9,172.6
XS GIS Cut Line= 4
 1651481.7795815534149.5789799991651569.91162309534137.656759754
1651745.66910903534095.8589399521651891.45069631534060.868149514
#Sta/Elev= 30
       0  956.87    10.3  947.85    17.3  942.85    30.2  930.59      60  908.06
    79.8  895.08    93.2  888.49    98.3  886.48   109.2  883.47   123.5  878.31
     137  875.08   163.7  867.36   174.6  865.96   204.3  865.23  213.41 862.995
   224.7   862.1   231.4  862.23  235.08 862.995   248.3  867.04   271.9  870.95
     282  871.89   291.7  874.67   302.6  880.67   312.4  884.03   319.5  887.63
   352.9  908.04   383.2  921.44   396.7  928.26   406.8  930.58   419.5  937.22
#Mann= 5, -1 ,  0
       0     0.1       0   88.93    0.08       0  158.93     0.1       0
  213.41   0.045       0  235.08     0.1       0
Bank Sta=213.41,235.08
XS Rating Curve= 0 ,0
Exp/Cntr(USF)=0,0
Exp/Cntr=0.3,0.1

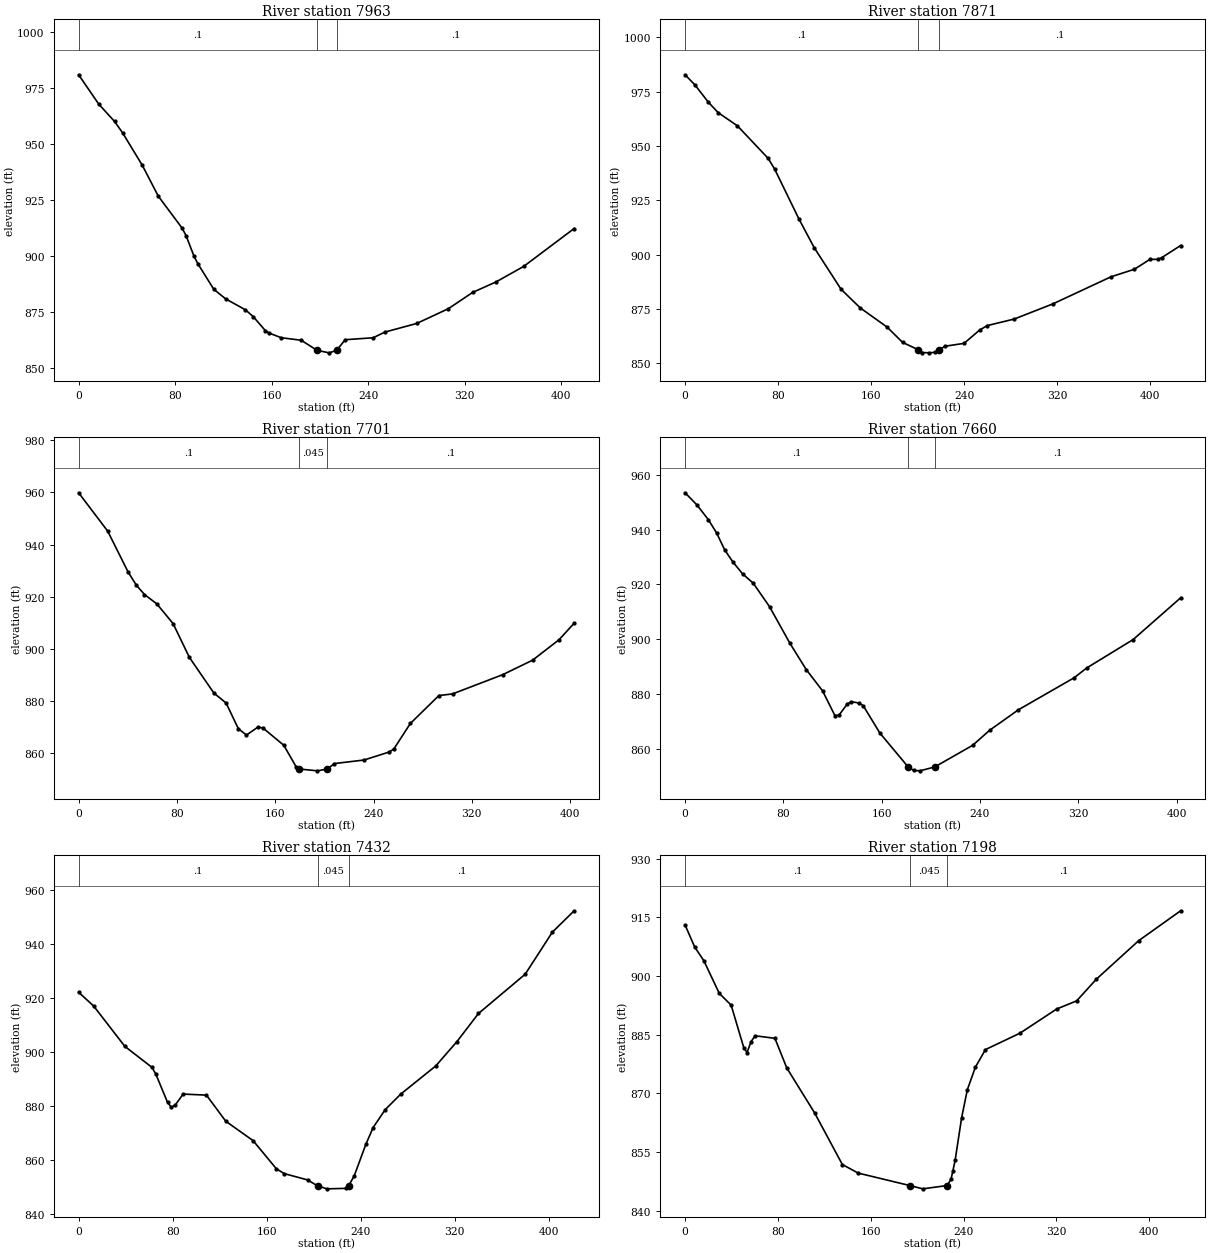
Type RM Length L Ch R = 1 ,7963    ,90,91.2,90.5
XS GIS Cut Line= 4
1651481.91185772 534262.486536811651655.25830017534272.005427887
1651712.37324946534263.3239555931651891.36359071534254.950615344
#Sta/Elev= 30
       0  980.91    16.7  967.78    29.8  960.04    36.4     955    52.8  940.44
      66  926.69    85.7  912.44      89  909.09    95.5  900.01    98.8  896.49
     112  885.08   121.8  880.82   138.2  875.92   144.8  872.81   154.7  866.63
     158   865.5   167.8  863.46   184.4  862.33   197.6  857.81   207.6   856.7
  213.73  857.81   220.9  862.57     244  863.43   253.8  865.98   280.1  869.82
   306.4  876.43   326.5   883.7   345.8  888.36   368.8  895.32   410.6  912.24
#Mann= 3, -1 ,  0
       0     0.1       0   197.6   0.045       0  213.73     0.1       0
Bank Sta=197.6,213.73
XS Rating Curve= 0 ,0
Exp/Cntr(USF)=0,0
Exp/Cntr=0.3,0.1

Type RM Length L Ch R = 1 ,7871    ,172.4,170.5,168.9
XS GIS Cut Line= 6
1651483.52664052534380.3860561481651570.37915711534369.765014388
1651644.90558286534361.3506611371651744.14390144534348.977654391
1651818.25202094534336.8553033111651904.98872411534319.791689136
#Sta/Elev= 30
       0  982.73     8.5  978.04    19.9  970.19    28.4  965.33    44.9  959.29
    71.3  944.34    76.9  939.44    97.8  916.47     111  903.19   134.1  884.06
   150.6  875.48   173.7  866.66   186.9  859.66  200.32856.2713   203.5  854.98
   210.1  854.83   214.7  855.06  218.51856.2692   223.5  857.87   239.8  859.19
   253.1  865.26   259.7  867.36   282.9  870.37   316.1  877.33   366.2  889.82
   386.3  893.28   399.6  897.84   406.3  897.82   409.7  898.59     426   904.2
#Mann= 3, -1 ,  0
       0     0.1       0  200.32   0.045       0  218.51     0.1       0
Bank Sta=200.32,218.51
XS Rating Curve= 0 ,0
Exp/Cntr(USF)=0,0
Exp/Cntr=0.3,0.1

Type RM Length L Ch R = 1 ,7701    ,41.2,41.3,41.1
XS GIS Cut Line= 3
1651537.44497153534555.4446510391651688.16340085534532.083294494
1651927.80570347534458.231264128
#Sta/Elev= 30
       0  959.83    23.7   945.1    40.3  929.44      47  924.41    53.6  920.84
    63.6  917.28    76.9   909.7    90.1  896.78   110.1  883.08     120  879.29
     130  869.42   136.6     867   145.7  869.98   149.9  869.75     167  863.08
   177.3  854.59  179.25 854.005   194.4  853.29  202.41854.0067   208.2  856.08
   232.2  857.43   252.8  860.51   256.5  861.65     270  871.45   293.2  882.14
   304.3  882.76   345.1  890.13   369.5   895.7     391  903.53   403.3  909.85
#Mann= 3, -1 ,  0
       0     0.1       0  179.25   0.045       0  202.41     0.1       0
Bank Sta=179.25,202.41
XS Rating Curve= 0 ,0
Exp/Cntr(USF)=0,0
Exp/Cntr=0.3,0.1

Type RM Length L Ch R = 1 ,7660    ,223.4,227.4,228.2
XS GIS Cut Line= 3
1651548.74885373534595.0082387351651699.46728305 534571.64688219
1651939.10958566534497.794851825
#Sta/Elev= 30
       0  953.48     9.5  949.11    18.9  943.67    25.6  938.85    32.2  932.65
    38.9   928.2    46.8  923.87    55.5  920.44    68.7  911.89    85.3  898.52
    98.6   888.9   111.9  881.12   121.9  872.12   125.2  872.22   131.8  876.22
   135.1   877.2   141.8  876.66   145.1  875.61   158.6  865.68  181.54853.3368
     186  852.08   191.1  851.92  203.14 853.337   234.1  861.26   247.8  866.72
   271.2   874.2   316.5  885.88   326.8  889.48   364.6  899.85   403.3  915.11
#Mann= 3, -1 ,  0
       0     0.1       0  181.54   0.045       0  203.14     0.1       0
Bank Sta=181.54,203.14
XS Rating Curve= 0 ,0
Exp/Cntr(USF)=0,0
Exp/Cntr=0.3,0.1

Type RM Length L Ch R = 1 ,7432    ,225.8,234.5,239.7
XS GIS Cut Line= 2
1651597.38727465534795.1084367781652015.66879624 534742.80790125
#Sta/Elev= 30
       0  922.24    12.8  917.13    39.3  902.18    62.4  894.38    65.7  891.85
    75.6  881.43    78.9  879.53    82.3  880.48    88.9  884.48   108.7   884.1
   125.2  874.39   148.4  867.22   168.2  856.78   174.8     855   194.7  852.65
  203.24850.4551   211.2  849.34   227.7  849.52  229.56850.4557   234.3  854.02
   244.3  865.84   250.5  872.07   260.8  878.72     274  884.48   303.8  894.93
   321.7   903.9   340.1  914.37   379.8  928.92     403  944.56   421.5  952.46
#Mann= 3, -1 ,  0
       0     0.1       0  203.24   0.045       0  229.56     0.1       0
Bank Sta=203.24,229.56
XS Rating Curve= 0 ,0
Exp/Cntr(USF)=0,0
Exp/Cntr=0.3,0.1

Type RM Length L Ch R = 1 ,7198    ,299.4,290.7,274.6
XS GIS Cut Line= 6
1651585.10122526534935.8953207581651669.52198817534960.709903672
1651741.77840534534982.2321703431651835.91896509 535016.25736475
1651906.11698742535042.638873667  1651993.579739535056.066340253
#Sta/Elev= 30
       0  913.03     8.3   907.4    16.2  903.88    29.4  895.59    39.7  892.55
    50.6  881.64    53.4  880.45    56.8   883.2    60.3  884.73    77.4  884.08
    87.6  876.52   111.6  865.03   135.5  851.83   149.2  849.64  193.48846.4722
   204.8  845.62  226.01846.4705   229.2  848.18   230.7   850.1   232.7  852.95
   238.3  863.82   243.2  870.94   250.1  876.68   258.8   881.2   288.6   885.4
   320.2  891.57   337.4  893.65   354.3  899.17   390.8  909.02     427  916.67
#Mann= 3, -1 ,  0
       0     0.1       0  193.48   0.045       0  226.01     0.1       0
Bank Sta=193.48,226.01
XS Rating Curve= 0 ,0
Exp/Cntr(USF)=0,0
Exp/Cntr=0.3,0.1

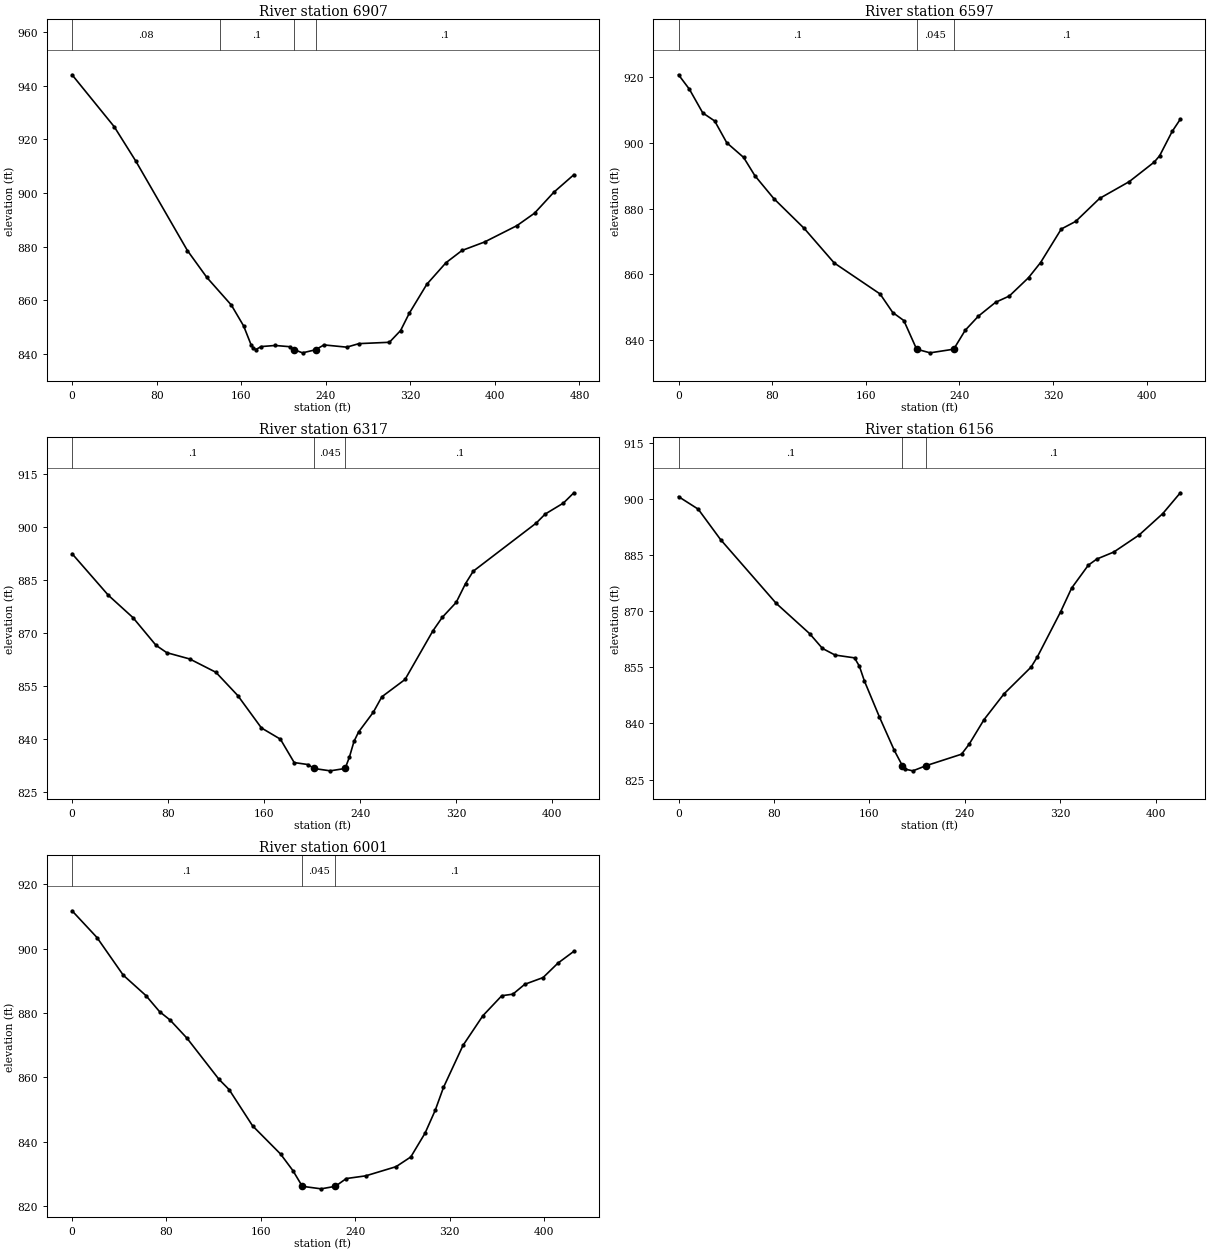
Type RM Length L Ch R = 1 ,6907    ,309.3,309.7,302.1
XS GIS Cut Line= 3
1651612.30622335 535389.153272511651842.86403371535155.929302761
1651972.70232996535087.593232499
#Sta/Elev= 30
       0  944.13    39.9  924.73    60.3   911.9   109.1  878.52   127.5  868.47
   150.7  858.14   162.3  850.36   169.5  843.17   171.6  842.08   173.9  841.56
   178.9  842.66   192.1  843.07     206  842.61   210.4841.4532     218  840.32
   230.3841.4565   238.3  843.28   259.8  842.44   271.4  843.76   300.2  844.26
   310.8  848.65   318.9  855.03   335.6  865.92   353.7  873.96   368.9  878.54
   390.2   881.7   420.8   887.8   437.5  892.46   455.7  900.26   474.7  906.82
#Mann= 4, -1 ,  0
       0    0.08       0     140     0.1       0   210.4   0.045       0
   230.3     0.1       0
Bank Sta=210.4,230.3
XS Rating Curve= 0 ,0
Exp/Cntr(USF)=0,0
Exp/Cntr=0.3,0.1

Type RM Length L Ch R = 1 ,6597    ,270.9,280.5,285
XS GIS Cut Line= 6
1651893.18558285535575.5511936691651937.19435309535499.593668416
1651971.07715935535432.6587629171652019.48782368 535345.15795368
1652066.18884575535284.4307129231652123.06471625535215.642136589
#Sta/Elev= 30
       0  920.68     9.3  916.28    20.7  909.09    30.9  906.63    41.2  900.02
    55.6  895.56    65.2  890.02    81.4  883.05   107.3  874.01     133  863.48
   172.2  854.05     183  848.42   192.5  845.97  203.41 837.275   214.9  836.16
   235.1837.2725   244.9  843.01   256.2  847.32   270.9  851.53   282.6  853.43
     299     859   309.3   863.6     327   873.8   339.3  876.11   359.7  883.09
   385.1  888.21   406.4  894.14     411  896.05   421.7  903.44   428.7  907.18
#Mann= 3, -1 ,  0
       0     0.1       0  203.41   0.045       0   235.1     0.1       0
Bank Sta=203.41,235.1
XS Rating Curve= 0 ,0
Exp/Cntr(USF)=0,0
Exp/Cntr=0.3,0.1

Type RM Length L Ch R = 1 ,6317    ,161.4,161.4,159.7
XS GIS Cut Line= 3
1652025.98682642535665.148783505  1652242.833173 535534.00638317
1652381.87858171535446.176750753
#Sta/Elev= 30
       0  892.54    30.2  880.78    50.8  874.42    69.9  866.61    78.9  864.52
      98  862.74   119.8  858.97     138  852.39   157.7  843.22   173.5  840.04
     185  833.42   196.5  832.86  201.43831.7442     215  831.08  227.42831.7474
     231     835   234.8  839.42   238.6  842.07   250.9  847.68     258  852.04
   277.3  856.94   300.5   870.7   308.3  874.52   319.9  878.75   327.7  884.09
   334.1  887.58   386.5  901.19     394  903.75   409.2  906.87   417.9  909.78
#Mann= 3, -1 ,  0
       0     0.1       0  201.43   0.045       0  227.42     0.1       0
Bank Sta=201.43,227.42
XS Rating Curve= 0 ,0
Exp/Cntr(USF)=0,0
Exp/Cntr=0.3,0.1

Type RM Length L Ch R = 1 ,6156    ,152.4,154.9,155.3
XS GIS Cut Line= 2
1652124.23286761535819.3520900381652454.51090717535558.851101091
#Sta/Elev= 30
       0  900.66    16.5  897.31    35.2  889.19    81.9  872.11   109.9  864.02
   120.6  860.08   131.2   858.3   147.5  857.55   151.6  855.31   155.8  851.36
   168.4  841.73   180.9  832.78  187.57828.7449   189.5  827.82   196.4  827.34
  207.74828.7454   237.2  831.79   243.6  834.47   256.1  841.05   272.8  847.92
   295.5  855.08   300.8  857.83   320.2  869.83   329.5  876.21   343.5  882.34
   350.6  883.97   364.8  885.84   386.1  890.41   405.9  896.13   420.6  901.69
#Mann= 3, -1 ,  0
       0     0.1       0  187.57   0.045       0  207.74     0.1       0
Bank Sta=187.57,207.74
XS Rating Curve= 0 ,0
Exp/Cntr(USF)=0,0
Exp/Cntr=0.3,0.1

Type RM Length L Ch R = 1 ,6001    ,270.6,266.9,263.2
XS GIS Cut Line= 6
1652203.10983175535923.7913108321652277.76060109535877.787137762
1652341.37005392535837.8239630911652423.65466626535780.982213259
 1652484.7933235535737.5416833461652556.12126485535686.860682338
#Sta/Elev= 30
       0  911.78    21.1  903.47    43.4  891.75    62.6  885.41    74.2   880.4
    83.1   877.8    97.4  872.16   124.5  859.37   133.1  856.18     153   844.9
   176.7  836.14   187.2  830.97  195.11826.0986   211.1  825.31  223.19826.0992
   232.4  828.51   248.9  829.35   274.6   832.2   287.1  835.23   299.2  842.64
   307.8  849.74   314.8  856.85   331.3  869.89   348.2  879.15   364.2  885.36
   373.6  885.85   383.7  888.92   399.2  891.01   411.8   895.5   425.3  899.17
#Mann= 3, -1 ,  0
       0     0.1       0  195.11   0.045       0  223.19     0.1       0
Bank Sta=195.11,223.19
XS Rating Curve= 0 ,0
Exp/Cntr(USF)=0,0
Exp/Cntr=0.3,0.1