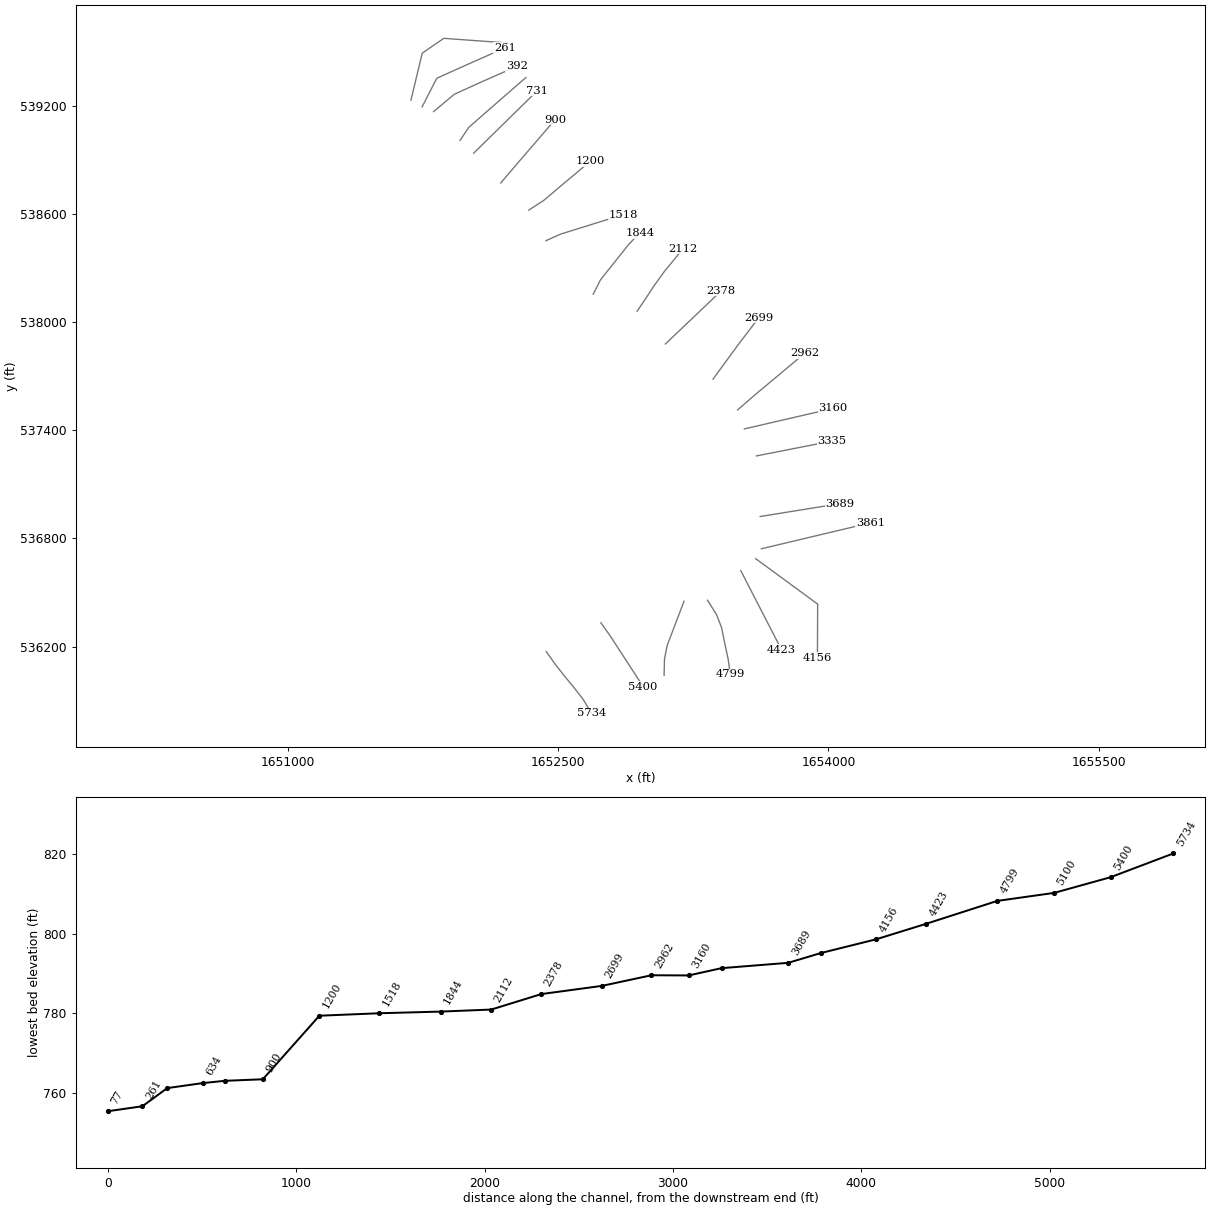
HEC-RAS study BurchRnI.prj: BurchRnI

--- BurchRnI.g01 (geometry) --- (continued)

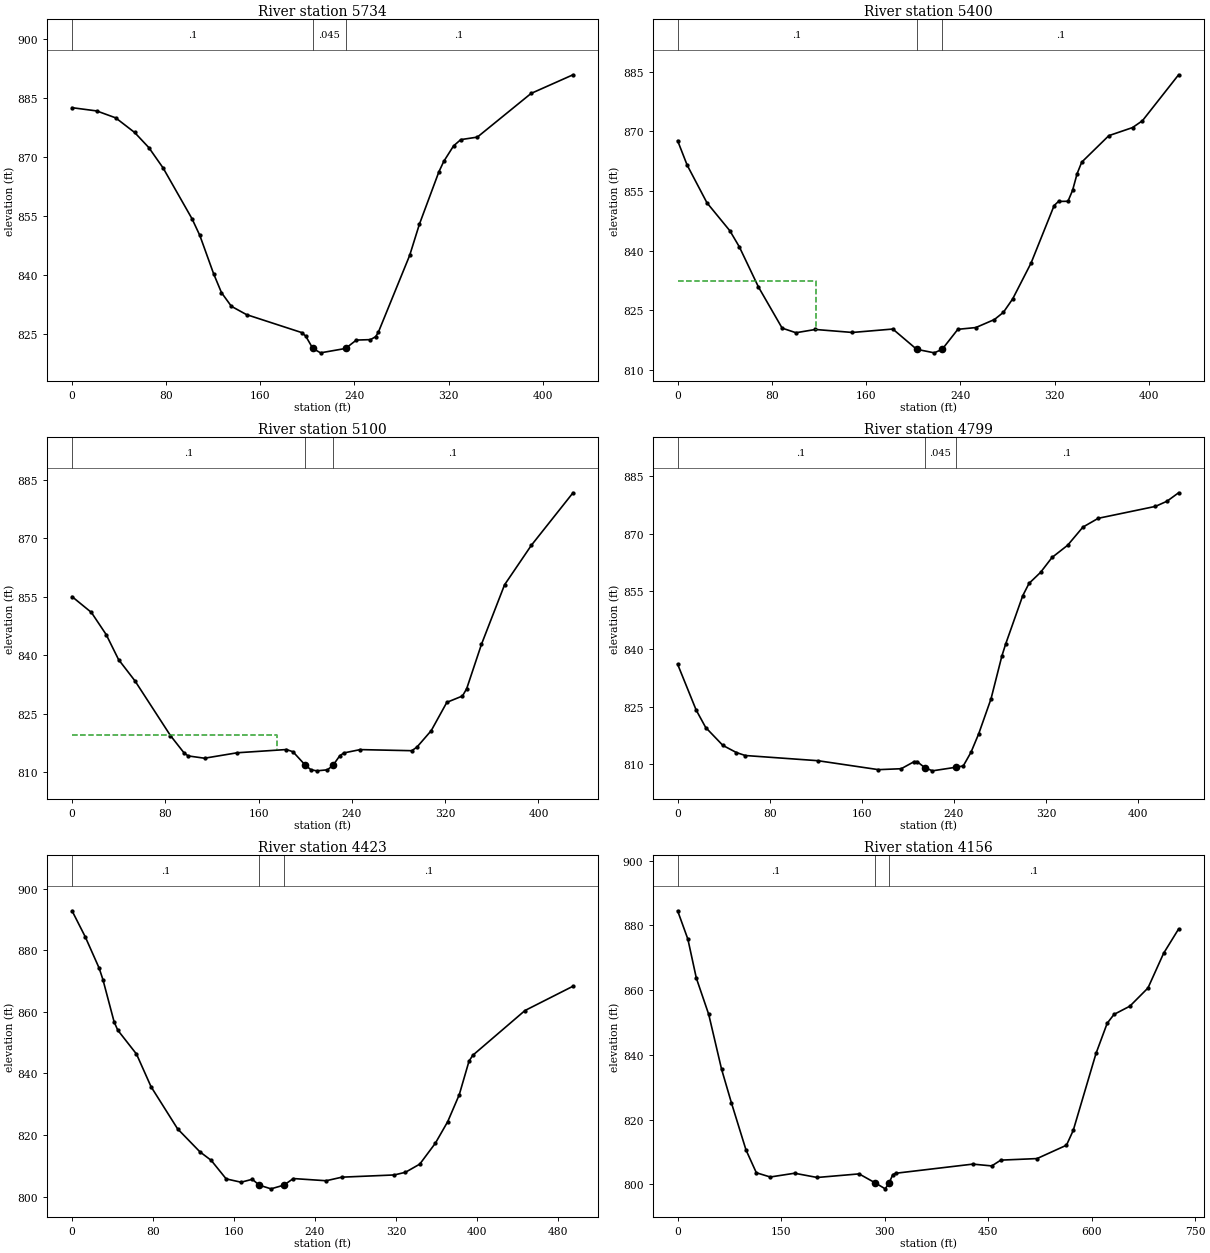
Type RM Length L Ch R = 1 ,5734    ,334.8,333.8,330.9
XS GIS Cut Line= 6
1652433.49918716536171.8261132691652484.35735317536100.403355852
 1652530.6538485 536041.377883361652593.97688458  535963.9817127
1652639.77666174535904.5494168551652684.74704426535828.894384444
#Sta/Elev= 30
       0  882.62      21  881.79    37.1  880.03    53.2  876.31    65.3  872.45
    77.4  867.28     102  854.34   108.6  850.11   120.3  840.38     127  835.56
   135.4  832.09   148.3  829.97     195  825.42   198.5  824.54  204.63821.3628
   211.2  820.25   232.4821.3626   241.6   823.5   253.6  823.61     258  824.36
   260.3   825.5   286.9  845.04   295.2     853   311.7  866.28   315.9  868.97
   324.2   872.9   330.3  874.49   344.4  875.13   390.1  886.25   425.7  890.99
#Mann= 3, -1 ,  0
       0     0.1       0  204.63   0.045       0   232.4     0.1       0
Bank Sta=204.63,232.4
XS Rating Curve= 0 ,0
Exp/Cntr(USF)=0,0
Exp/Cntr=0.3,0.1

Type RM Length L Ch R = 1 ,5400    ,310.4,300,288.5
XS GIS Cut Line= 6
1652736.80823943536331.9555207491652787.66017184536260.647264421
1652828.50523451536197.7451592531652882.96575551536113.875904426
1652923.81147434536050.9741273371652971.46459426535977.588775426
#Sta/Elev= 30
       0  867.65     8.1  861.49    24.9  852.01    44.4  844.95    52.4  840.91
    68.6  830.82    88.7  820.47   100.4  819.31   116.9  820.13   148.3  819.38
   182.6  820.24  202.86815.1379   217.8  814.25  224.48815.1387   237.8  820.17
     253  820.61   268.8  822.63   276.4  824.43   284.3  827.82   299.9  836.84
   319.5  851.32   323.2  852.36   331.2  852.39   335.1  855.11     339  859.35
   342.9  862.24   365.9  868.91     386  870.94   394.4  872.66   425.1  884.23
#Mann= 3, -1 ,  0
       0     0.1       0  202.86   0.045       0  224.48     0.1       0
#XS Ineff= 2 , 0
           117.3  832.23
Permanent Ineff=
       F       F
Bank Sta=202.86,224.48
XS Rating Curve= 0 ,0
Exp/Cntr(USF)=0,0
Exp/Cntr=0.3,0.1

Type RM Length L Ch R = 1 ,5100    ,294.6,301.2,308.3
XS GIS Cut Line= 6
1653198.54353642536451.2331693321653167.39399242536369.465616345
1653140.69358651536299.3791423441653105.09326401536205.930838421
1653090.19499984536131.5556590861653087.86954518536040.316012174
#Sta/Elev= 30
       0  855.02    16.6  850.96    29.3  845.27    39.9  838.86      54  833.38
    84.4  819.35    96.1  814.89    99.6  814.13   113.6  813.54   141.7  814.94
   183.9  815.77   189.5  815.19  200.16811.7119   204.9  810.58   209.8   810.3
     219  810.56  223.78811.7134   229.5  814.13     233  814.89   247.1  815.75
   291.3  815.47   295.7  816.37     308  820.61   321.4  827.88   334.8  829.51
   338.4  831.37   351.1  842.78   370.9  858.05   393.9   868.2   429.6  881.67
#Mann= 3, -1 ,  0
       0     0.1       0  200.16   0.045       0  223.78     0.1       0
#XS Ineff= 2 , 0
          176.17  819.39
Permanent Ineff=
       F       F
Bank Sta=200.16,223.78
XS Rating Curve= 0 ,0
Exp/Cntr(USF)=0,0
Exp/Cntr=0.3,0.1

Type RM Length L Ch R = 1 ,4799    ,373.2,375.9,379.7
XS GIS Cut Line= 6
1653328.91138592536457.1015959231653378.96738817 536377.29696551
1653407.18091442536304.3807727551653427.09196384536206.355706334
1653443.05387418536133.0710760061653455.55516151536046.327155009
#Sta/Elev= 30
       0  836.03    16.1  824.11    24.4  819.56    39.3  814.91      51  813.06
    58.7  812.28   121.8  810.93   174.4   808.6   194.2  808.84   205.4  810.68
   207.9  810.71   214.6  809.14   221.3  808.29   241.6  809.22   248.1  809.57
   254.8  813.12   261.5  817.93   272.2  827.03   281.6  838.14   284.9  841.27
   299.7  853.82   305.2  857.05   315.2  859.91   325.2   863.8   338.7  866.96
     352  871.69   365.3  873.98     415  877.08     425  878.42   435.1  880.62
#Mann= 3, -1 ,  0
       0     0.1       0   214.6   0.045       0   241.6     0.1       0
Bank Sta=214.6,241.6
XS Rating Curve= 0 ,0
Exp/Cntr(USF)=0,0
Exp/Cntr=0.3,0.1

Type RM Length L Ch R = 1 ,4423    ,257.4,267,267.4
XS GIS Cut Line= 2
1653513.58240648536621.4725126411653740.28826645536181.461151203
#Sta/Elev= 30
       0  892.82      13  884.41    26.8   874.2    30.5   870.5    41.6  856.74
    45.2  854.06    63.7   846.3    78.1  835.69   104.3  822.03   126.4  814.55
   137.5   811.8   152.3  805.78     167   804.7   178.1  805.65     185803.7484
   196.6  802.55  209.27803.7488   218.7  805.89   251.1  805.18   266.7  806.34
   318.4  807.06   329.4  807.92   343.6  810.58     359  817.37   371.2  824.37
   382.6  833.11   392.2  843.96   395.9  845.89   447.5  860.43     495  868.33
#Mann= 3, -1 ,  0
       0     0.1       0     185   0.045       0  209.27     0.1       0
Bank Sta=185,209.27
XS Rating Curve= 0 ,0
Exp/Cntr(USF)=0,0
Exp/Cntr=0.3,0.1

Type RM Length L Ch R = 1 ,4156    ,279,294.9,300.1
XS GIS Cut Line= 3
1653596.13263626536688.0473282491653940.59312561536435.607118083
1653939.08783217536136.532609739
#Sta/Elev= 30
       0  884.54    14.9  875.76    27.1  863.76    45.1  852.51    63.7   835.6
    77.9  825.26    99.1  810.65   114.1  803.59   134.3  802.28   169.5  803.44
   202.3  802.13     263  803.24  285.64 800.552   300.9  798.62  306.83800.5555
   311.8  802.99   315.9  803.43   427.9  806.26   455.3   805.7   468.4  807.49
   520.9  807.97   563.6   812.1   573.4  816.68   606.4  840.46   622.6  849.78
   632.5  852.52   655.5  855.07   681.7  860.68   704.4  871.41   726.1  878.91
#Mann= 3, -1 ,  0
       0     0.1       0  285.64   0.045       0  306.83     0.1       0
Bank Sta=285.64,306.83
XS Rating Curve= 0 ,0
Exp/Cntr(USF)=0,0
Exp/Cntr=0.3,0.1

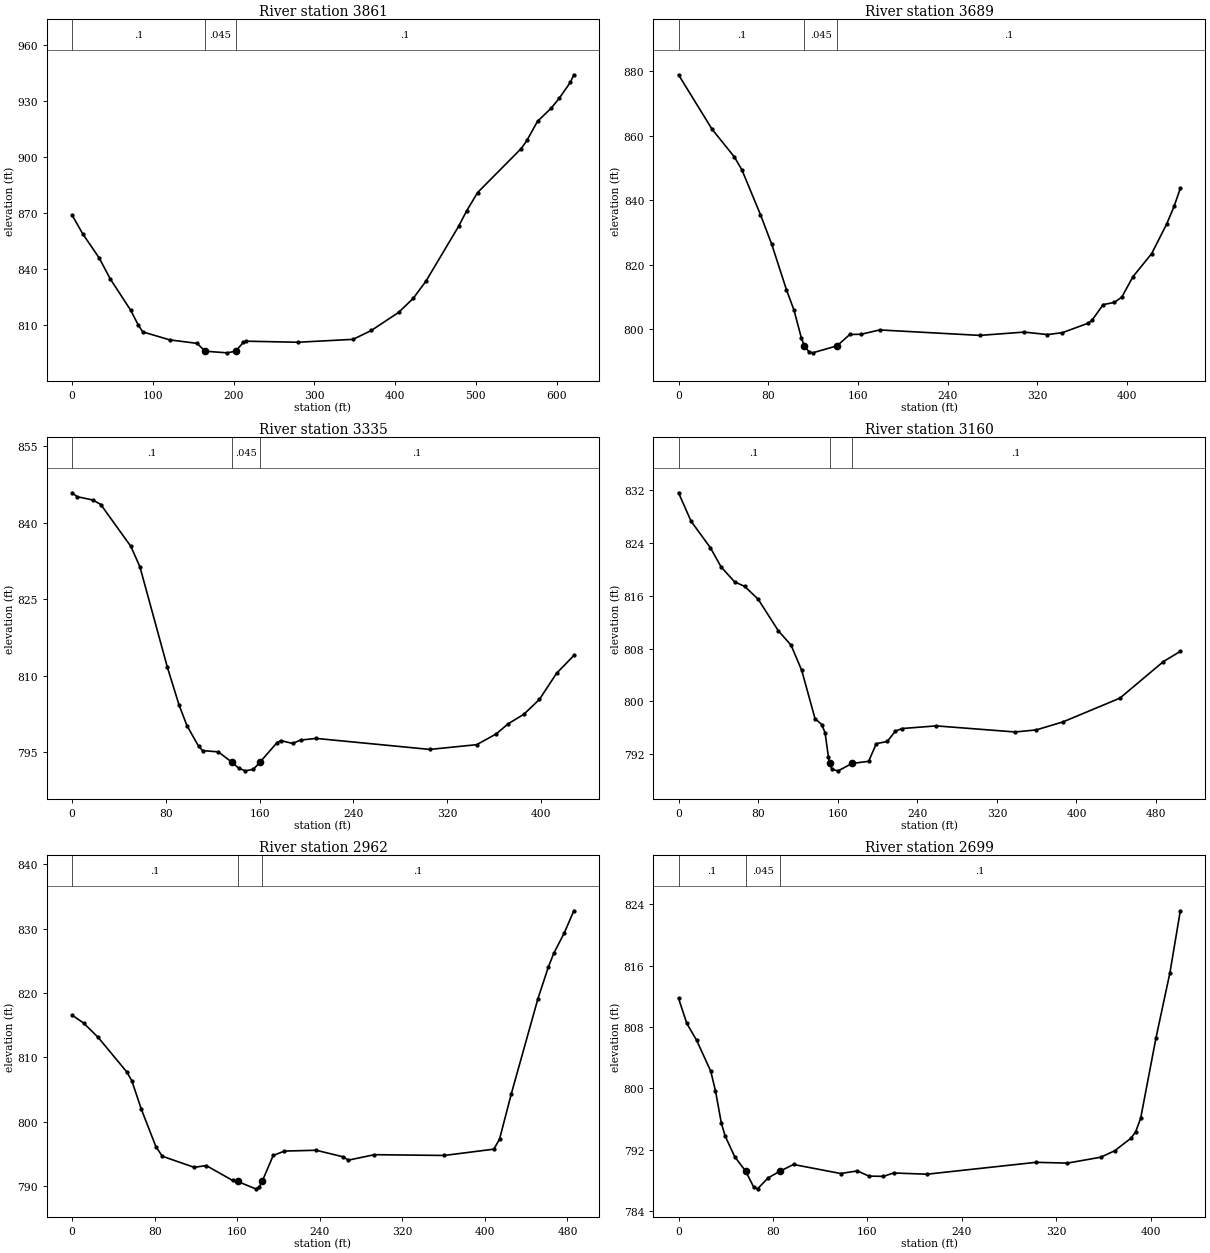
Type RM Length L Ch R = 1 ,3861    ,169.4,172.3,168.6
XS GIS Cut Line= 2
1653627.94984467536742.7486471521654232.60981274536886.457150892
#Sta/Elev= 30
       0  868.94    13.3  858.82    33.6  845.95    47.1  834.88    72.8  817.83
    81.9   810.1    87.5  806.36   121.2  802.07     155   800.2   164.7796.0167
   192.1  795.14  202.56796.0151   212.3  800.82   215.7  801.38   279.7  800.81
     348  802.37   370.8  807.15   404.5  816.82   422.5  824.31   438.2  833.47
   478.7  862.87   488.8  871.28   502.3  881.01   556.3  904.58   563.3   908.9
   576.5  919.17   593.4   926.2   603.5  931.56     617  939.96   621.5  944.09
#Mann= 3, -1 ,  0
       0     0.1       0   164.7   0.045       0  202.56     0.1       0
Bank Sta=164.7,202.56
XS Rating Curve= 0 ,0
Exp/Cntr(USF)=0,0
Exp/Cntr=0.3,0.1

Type RM Length L Ch R = 1 ,3689    ,351,353.5,350.7
XS GIS Cut Line= 2
1653621.26549403536921.8743362061654063.16997627536993.158300177
#Sta/Elev= 30
       0  878.91    29.9  862.03    49.8  853.44    56.5  849.45    73.1  835.52
    83.1  826.38    96.3  812.22     103  805.93   109.6  797.25  112.24794.8633
   116.3  793.03   119.6  792.69  141.37794.8607   152.8  798.38   162.8  798.45
   179.4  799.79   268.7   798.1   308.3  799.12     329  798.36   342.3  798.93
   365.5  801.89   368.8  802.79   378.8  807.64   388.8  808.34   395.4  809.98
   405.4  816.33     422  823.44   435.3  832.54     442  838.07   447.6  843.71
#Mann= 3, -1 ,  0
       0     0.1       0  112.24   0.045       0  141.37     0.1       0
Bank Sta=112.24,141.37
XS Rating Curve= 0 ,0
Exp/Cntr(USF)=0,0
Exp/Cntr=0.3,0.1

Type RM Length L Ch R = 1 ,3335    ,172.1,175.2,173.2
XS GIS Cut Line= 2
1653600.52510666537258.2984232531654020.79821624537340.724767588
#Sta/Elev= 30
       0  845.88     4.4  845.11    17.8  844.46    24.5  843.58    50.2  835.36
    57.9  831.37    81.3   811.7    91.3  804.28      98  800.24     108  796.17
   111.4  795.32   124.8  795.07  136.41793.0427   142.4  791.84     148  791.35
   154.8  791.66  160.37 793.043   174.9  796.87   178.2  797.28   188.3  796.72
     195  797.38   208.3  797.71   305.3  795.55   345.4  796.48   362.1   798.6
   372.2  800.57   385.6  802.44   398.9  805.35   413.5  810.47   428.3  813.97
#Mann= 3, -1 ,  0
       0     0.1       0  136.41   0.045       0  160.37     0.1       0
Bank Sta=136.41,160.37
XS Rating Curve= 0 ,0
Exp/Cntr(USF)=0,0
Exp/Cntr=0.3,0.1

Type RM Length L Ch R = 1 ,3160    ,190.1,197.3,201.3
XS GIS Cut Line= 2
1653533.47272406537408.2203201691654024.92426157537521.795513503
#Sta/Elev= 30
       0  831.57    12.6  827.27      32  823.26    42.9  820.33    56.4  818.09
    66.5  817.41      80  815.48   100.2  810.72   113.1  808.52   123.8  804.72
   137.2  797.41     144  796.51   147.3  795.27   150.7  791.56   152.3  790.63
   154.1  789.72   160.5  789.51   174.4  790.63   191.1  790.95   198.8  793.62
   209.8  793.95     218  795.52   224.8  795.91     259  796.31   338.3  795.39
   359.5   795.7   386.4  796.91   443.6   800.5   487.4  806.04   504.4  807.58
#Mann= 3, -1 ,  0
       0     0.1       0   152.3   0.045       0   174.4     0.1       0
Bank Sta=152.3,174.4
XS Rating Curve= 0 ,0
Exp/Cntr(USF)=0,0
Exp/Cntr=0.3,0.1

Type RM Length L Ch R = 1 ,2962    ,257.2,263.3,261.9
XS GIS Cut Line= 3
1653496.08366982537513.8432724551653596.43880639537600.589638796
1653867.76359992537827.337538274
#Sta/Elev= 30
       0  816.57    11.4  815.31    25.3   813.1    53.2   807.7    57.9  806.35
    67.2   801.9    81.2  796.13    87.4  794.63   118.4   792.9     130  793.18
   155.6  790.86   160.3  790.72   177.8  789.56   181.2  789.81  184.26  790.74
   194.9  794.75   205.8  795.43   236.5  795.56   262.8  794.53   267.6  794.02
     293  794.87   360.6  794.75   408.7  795.73   414.2  797.29   425.6  804.34
   451.4  819.13   461.6   824.1   466.7  826.16     477  829.38   486.2  832.79
#Mann= 3, -1 ,  0
       0     0.1       0   160.3   0.045       0  184.26     0.1       0
Bank Sta=160.3,184.26
XS Rating Curve= 0 ,0
Exp/Cntr(USF)=0,0
Exp/Cntr=0.3,0.1

Type RM Length L Ch R = 1 ,2699    ,321.2,321.3,316.6
XS GIS Cut Line= 6
1653359.55482525537684.5335973131653411.13411842 537755.21488639
1653455.34400375537815.7994108871653514.84126008537896.176874809
  1653560.348715 537955.814550811653613.59795233538025.277010314
#Sta/Elev= 30
       0  811.75       7  808.48    15.4  806.25    27.3  802.23    31.3  799.66
    36.3  795.43    39.5  793.77    47.6  791.07   56.85789.1825    63.8  787.07
    66.9  786.88      76  788.32   86.09789.1998    97.4  790.06   137.3  788.88
   151.4  789.22   161.3  788.54   173.5  788.51   182.2  788.95   210.3  788.79
   302.7  790.34   329.4  790.24   357.6  791.01   369.3  791.84   383.4  793.51
   387.2  794.34   391.4  796.09   404.4   806.6   416.2   815.1     425  823.18
#Mann= 3, -1 ,  0
       0     0.1       0   56.85   0.045       0   86.09     0.1       0
Bank Sta=56.85,86.09
XS Rating Curve= 0 ,0
Exp/Cntr(USF)=0,0
Exp/Cntr=0.3,0.1

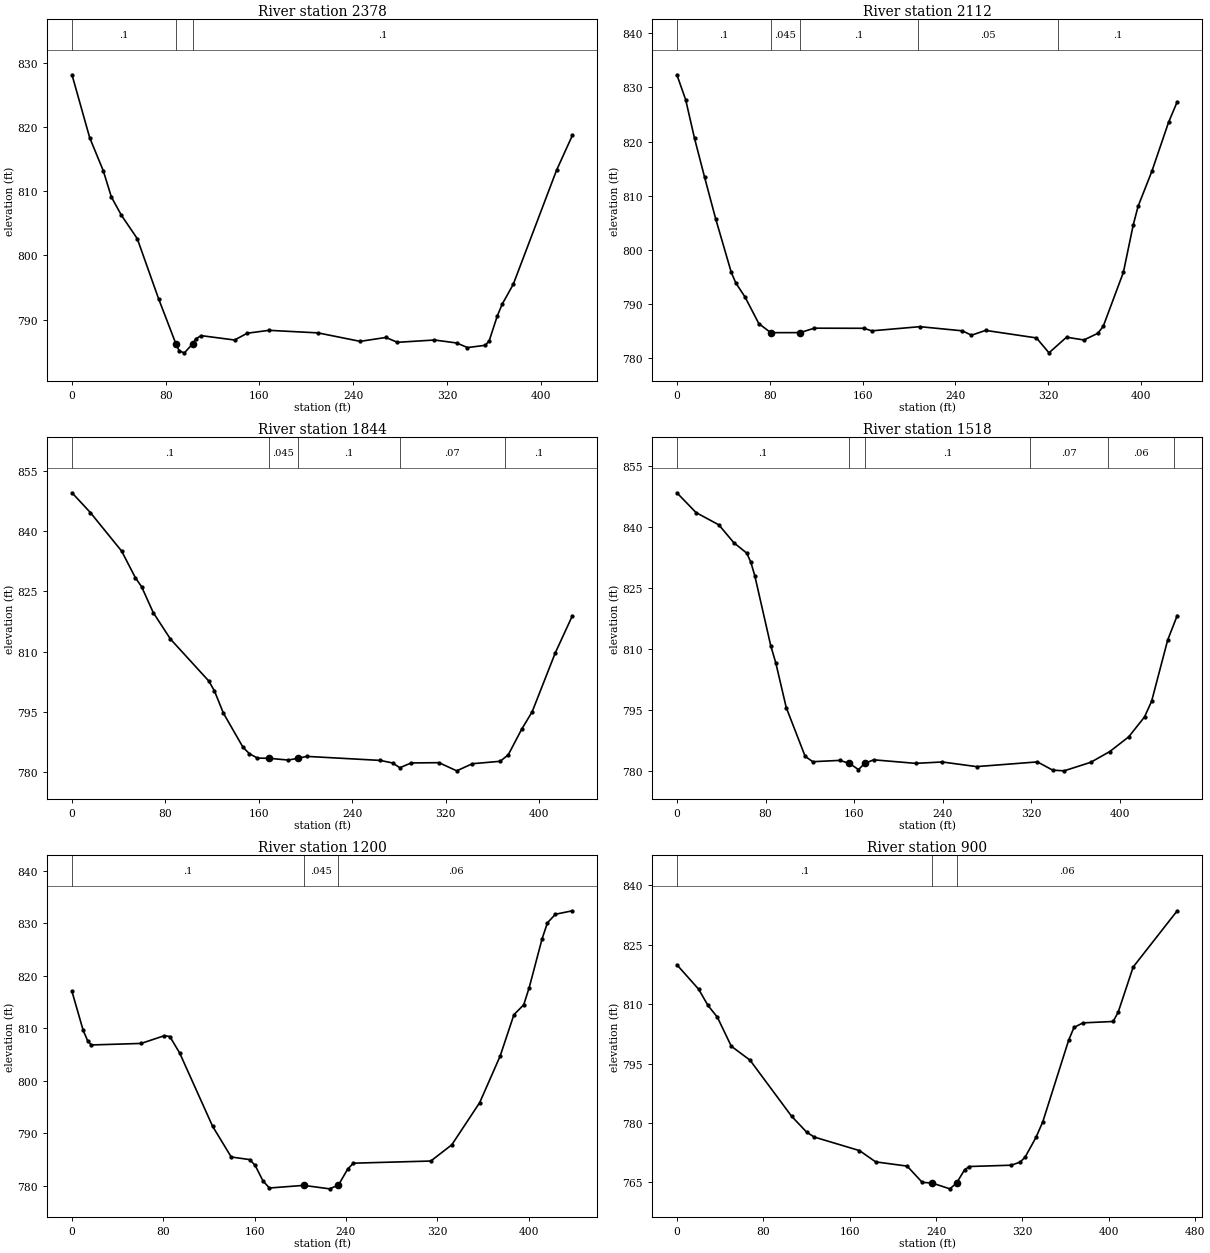
Type RM Length L Ch R = 1 ,2378    ,262.6,265.8,268
XS GIS Cut Line= 2
1653095.30908871537879.8545365711653404.57906347538174.362306464
#Sta/Elev= 30
       0  828.17    15.1  818.36    26.7  813.21    33.6  809.12    42.2  806.26
    55.7  802.63    73.9  793.26   88.65786.2498    91.6  785.09      96  784.82
   103.2  786.27   105.6     787   110.3   787.5   138.8  786.82   149.6  787.88
   168.2  788.33     210  787.93     246  786.61     268  787.22   277.7  786.46
   309.4  786.82   328.3  786.36   337.6  785.64   352.9     786   356.2  786.74
   363.1  790.61   367.2   792.4   376.7  795.52   413.6  813.28   427.1  818.71
#Mann= 3, -1 ,  0
       0     0.1       0   88.65   0.045       0   103.2     0.1       0
Bank Sta=88.65,103.2
XS Rating Curve= 0 ,0
Exp/Cntr(USF)=0,0
Exp/Cntr=0.3,0.1

Type RM Length L Ch R = 1 ,2112    ,267.9,268.7,266.4
XS GIS Cut Line= 6
1652937.87465189538061.4059251011652988.32533839538136.175132519
1653030.99946564538201.1477716021653089.85400672538282.867424434
1653137.41427905538340.8184240221653192.89710772538408.423931857
#Sta/Elev= 30
       0  832.35     7.6  827.71    15.2  820.59    23.9  813.38    33.4  805.73
    46.9  795.78    50.8  793.84    58.7  791.25    70.6  786.33   80.89  784.65
   106.1  784.66   118.5  785.48   161.1  785.46   167.9  784.99   209.4  785.76
     246  784.99   253.8  784.18     266  785.07   309.8  783.68   320.6  780.92
   335.7  783.81   350.7   783.3   362.6  784.52   367.3   785.8   384.7  795.81
   393.2  804.58   397.4  808.04   409.2  814.47   423.6  823.54   431.1  827.36
#Mann= 5, -1 ,  0
       0     0.1       0   80.89   0.045       0   106.1     0.1       0
  207.93    0.05       0  328.64     0.1       0
Bank Sta=80.89,106.1
XS Rating Curve= 0 ,0
Exp/Cntr(USF)=0,0
Exp/Cntr=0.3,0.1

Type RM Length L Ch R = 1 ,1844    ,326.3,325.4,319.1
XS GIS Cut Line= 4
1652694.36432659538156.3520940171652735.45906067 538236.93953126
1652891.46432609538432.6835623461652952.24701292538495.756270849
#Sta/Elev= 30
       0  849.49    15.7  844.59    42.5     835    54.3  828.37    59.6  826.15
    69.6   819.7    84.3  813.15   117.1  802.73     122  800.24   129.6  794.76
   146.4  786.27   151.9  784.67   158.8  783.57   168.3  783.53   185.2  783.09
  193.58 783.529     201     784   263.9     783   274.6  782.36   280.7  781.18
   290.4  782.37   314.2  782.44   329.4  780.41   342.8  782.18   366.6  782.78
   373.5  784.38   385.1  790.79     394  795.09   413.8  809.73   428.4  818.92
#Mann= 5, -1 ,  0
       0     0.1       0   168.3   0.045       0  193.58     0.1       0
  280.46    0.07       0  370.77     0.1       0
Bank Sta=168.3,193.58
XS Rating Curve= 0 ,0
Exp/Cntr(USF)=0,0
Exp/Cntr=0.3,0.1

Type RM Length L Ch R = 1 ,1518    ,295.4,318.1,315.8
XS GIS Cut Line= 3
1652431.81321646 538453.149557491652512.79533797 538489.66031124
1652859.13913346538597.455371249
#Sta/Elev= 30
       0  848.43    17.3  843.56    37.9  840.53    51.4  836.14    63.1  833.57
    66.7  831.36    70.3  828.04    84.7  810.81    89.3  806.53    98.7  795.57
   115.8  783.54   122.7  782.24   146.9  782.56  155.58 781.851   163.9   780.3
  169.74781.8672   177.7   782.7   215.5  781.83   239.5  782.17   270.5  781.03
   325.4  782.19   339.2  780.16   349.5  779.99   373.5  782.09   390.7  784.73
   407.9  788.38   422.1  793.27   428.5  797.14     443  812.21   451.6  818.21
#Mann= 6, -1 ,  0
       0     0.1       0  155.58   0.045       0  169.74     0.1       0
  318.83    0.07       0  388.83    0.06       0  448.83     0.1       0
Bank Sta=155.58,169.74
XS Rating Curve= 0 ,0
Exp/Cntr(USF)=0,0
Exp/Cntr=0.3,0.1

Type RM Length L Ch R = 1 ,1200    ,290,300.1,298.3
XS GIS Cut Line= 6
1652336.78869826538623.0841405841652419.73210192538676.911132678
1652478.47115767538726.7870171671652555.04744808538791.098896429
1652612.47974792 538839.333051921652679.48420709538895.606561422
#Sta/Elev= 30
       0  816.98     9.8  809.56    13.7  807.61    16.9  806.79    60.6  807.08
      81  808.56    85.7   808.4    94.3  805.27   123.2  791.29   139.5  785.44
   155.8  784.94   160.5  783.82   167.4  780.86     173  779.53     203  780.03
   225.7  779.37  233.44780.0896   241.6  783.15   246.6  784.26   314.4  784.67
   332.8  787.77   357.2   795.8   375.1  804.65   387.2  812.55   395.8  814.45
   400.6  817.72   411.9  827.03   416.6  830.08   423.6   831.7   438.4  832.36
#Mann= 3, -1 ,  0
       0     0.1       0     203   0.045       0  233.44    0.06       0
Bank Sta=203,233.44
XS Rating Curve= 0 ,0
Exp/Cntr(USF)=0,0
Exp/Cntr=0.3,0.1

Type RM Length L Ch R = 1 ,900     ,203.6,202.7,201.6
XS GIS Cut Line= 5
1652181.09576817538773.8444830681652311.48953626538926.698034674
1652376.86145276539002.3720959281652425.73602693539059.260433584
1652483.45507158539125.029659003
#Sta/Elev= 30
       0  819.96    20.1   813.8    28.8  809.68    37.5  806.71    50.4  799.38
    67.7  795.87   106.2  781.71   120.2  777.68   127.2  776.44   169.1  773.02
   184.1  770.17   213.3   769.1   227.2     765   236.5  764.82   252.8  763.36
  259.04  764.82   266.4  768.15   270.7     769   309.7  769.33     318  770.12
   322.6  771.41   332.6  776.36   338.9   780.3   362.8  800.87   367.8  804.13
   376.1  805.28     404  805.63   408.7  807.97   422.6  819.39   463.4  833.59
#Mann= 3, -1 ,  0
       0     0.1       0   236.5   0.045       0  259.04    0.06       0
Bank Sta=236.5,259.04
XS Rating Curve= 0 ,0
Exp/Cntr(USF)=0,0
Exp/Cntr=0.3,0.1

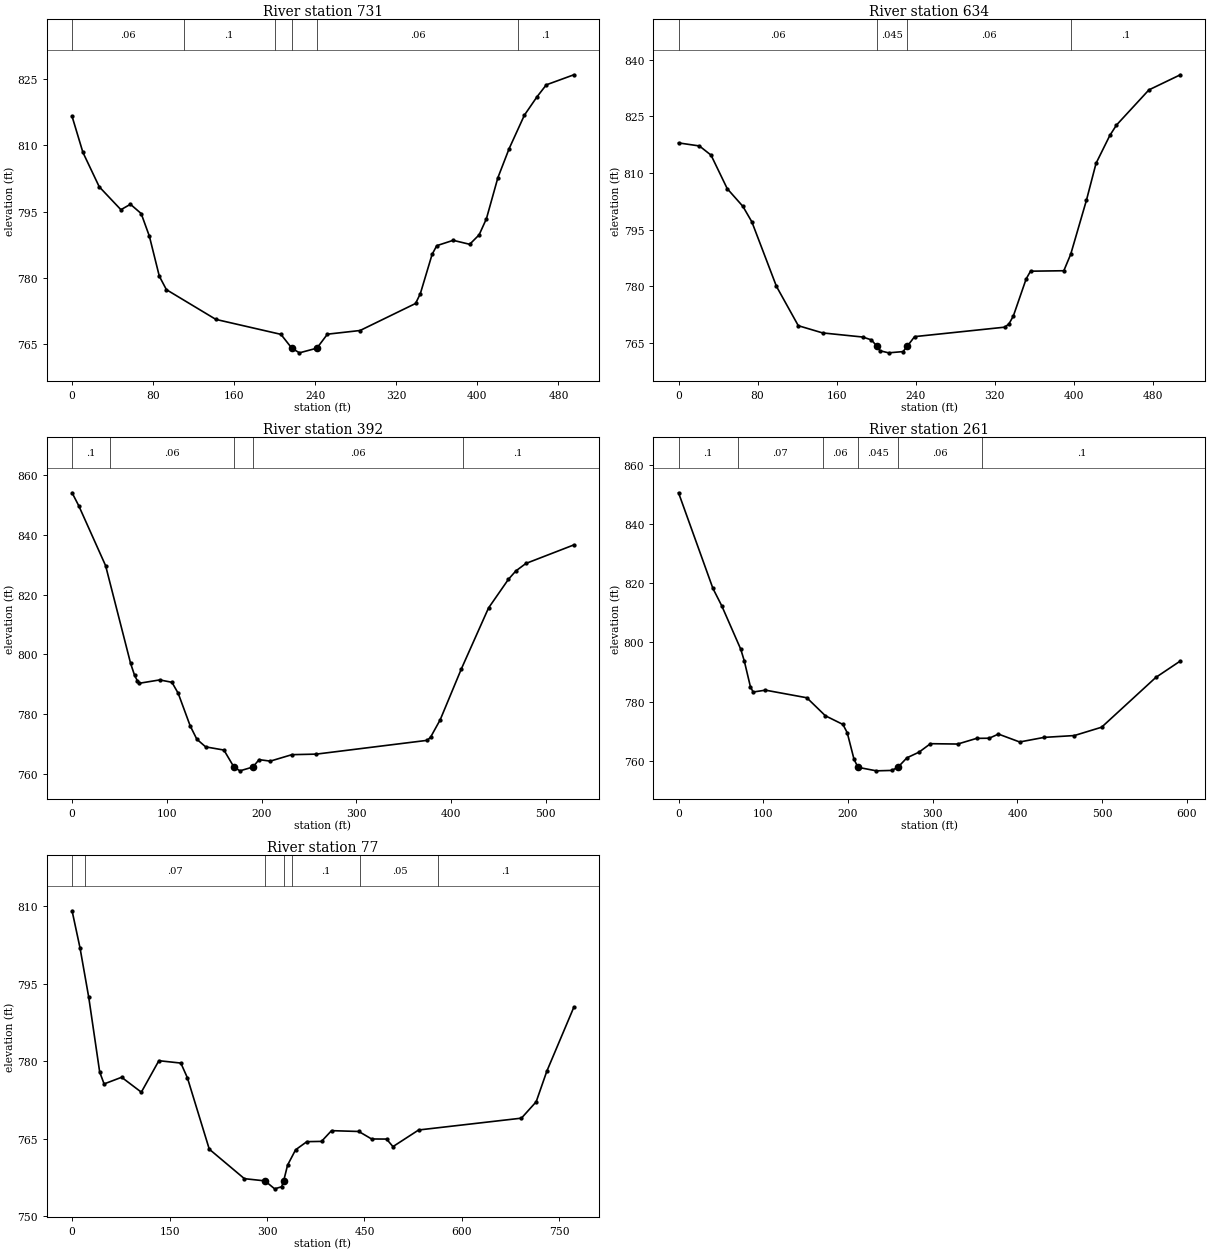
Type RM Length L Ch R = 1 ,731     ,116.9,116.1,114.1
XS GIS Cut Line= 2
1652030.59332225 538939.176696131652384.05630711539285.952543442
#Sta/Elev= 30
       0  816.56    10.7   808.4    26.8  800.61    48.2  795.41    57.6  796.64
    68.2  794.54    76.3   789.4    86.1  780.34    93.1  777.29   141.9  770.55
   206.1  767.16   216.9  764.01   224.4  762.97   241.6  764.03     252   767.2
   284.2  768.03     339  774.16   343.7  776.39   355.3  785.28   359.9  787.26
   376.1  788.47   392.4  787.57   401.7  789.71   408.9  793.36   420.2  802.65
   431.3  809.24   446.4  816.84   458.8  820.99     468  823.71   495.2  825.99
#Mann= 6, -1 ,  0
       0    0.06       0     110     0.1       0     200    0.06       0
   216.9   0.045       0   241.6    0.06       0     440     0.1       0
Bank Sta=216.9,241.6
XS Rating Curve= 0 ,0
Exp/Cntr(USF)=0,0
Exp/Cntr=0.3,0.1

Type RM Length L Ch R = 1 ,634     ,188.6,188.8,185.1
XS GIS Cut Line= 3
1651955.22298628539010.3873041521652003.91252145539083.089258487
1652320.75677227539359.255907763
#Sta/Elev= 30
       0  817.94    21.1  817.13    32.9   814.7    49.3  805.82    65.1  801.16
    74.2  797.05    99.1  779.98   121.2  769.58   145.8  767.67   186.5  766.58
   195.2  765.82  200.61764.1917   203.9  762.95   212.6   762.4   227.2  762.73
  231.59764.1938   238.9  766.69   330.1  769.19   334.4  770.07   338.8  772.13
   351.8  781.97   356.2     784   389.9  784.12   396.9   788.5   412.8  802.78
   422.5  812.53   436.5  819.93   443.2  822.66     476  831.96   507.8  835.96
#Mann= 4, -1 ,  0
       0    0.06       0  200.61   0.045       0  231.59    0.06       0
   397.5     0.1       0
Bank Sta=200.61,231.59
XS Rating Curve= 0 ,0
Exp/Cntr(USF)=0,0
Exp/Cntr=0.3,0.1

Type RM Length L Ch R = 1 ,392     ,134,131.5,124.1
XS GIS Cut Line= 4
1651808.18049967539170.0618185191651922.99513085 539266.17838787
1652071.07717474539333.4409228541652269.97151038539421.043875177
#Sta/Elev= 30
       0  853.96       7  849.67    35.4  829.63    61.8     797      66     793
    68.8  791.29    71.1  790.38    92.5  791.49   105.4   790.7     112  787.05
   124.7  776.14   131.7   771.7     141  769.14   160.3  768.08  170.84762.4166
   177.2  761.14   190.9762.4169   197.4  764.88   209.2  764.38   232.1  766.54
   257.8  766.72   375.1  771.33   378.6  772.46   388.6  778.18     411  795.22
   439.6  815.49   460.7  825.11   468.5  827.88   479.1  830.37   529.7  836.56
#Mann= 5, -1 ,  0
       0     0.1       0      40    0.06       0  170.84   0.045       0
   190.9    0.06       0  412.38     0.1       0
Bank Sta=170.84,190.9
XS Rating Curve= 0 ,0
Exp/Cntr(USF)=0,0
Exp/Cntr=0.3,0.1

Type RM Length L Ch R = 1 ,261     ,175.5,184.2,186.2
XS GIS Cut Line= 4
1651744.36271776539195.9890189471651825.68436465539354.904933847
1652004.74741901539435.5646625491652203.64175465539523.167614872
#Sta/Elev= 30
       0  850.59    40.6  818.24      51  812.37    73.4  797.71    77.5  793.84
    84.8  785.04      88  783.22   102.6  783.85   151.4  781.28   173.3  775.19
     194  772.26   199.1  769.46   207.1  760.48  211.77757.7612   233.5  756.57
   251.5  756.71  258.88757.7602   269.5  760.97   283.9   762.9   297.3  765.75
   329.5  765.63   351.8  767.55   366.7   767.6   377.5     769   402.6  766.33
   431.4  767.88   467.1   768.5   499.3  771.32   563.3  788.16   592.2  793.71
#Mann= 6, -1 ,  0
       0     0.1       0      70    0.07       0     170    0.06       0
  211.77   0.045       0  258.88    0.06       0  358.51     0.1       0
Bank Sta=211.77,258.88
XS Rating Curve= 0 ,0
Exp/Cntr(USF)=0,0
Exp/Cntr=0.3,0.1

Type RM Length L Ch R = 1 ,77      ,,,
XS GIS Cut Line= 4
1651682.37744519539233.4363400911651745.17679074539494.681617576
1651864.91420959539576.7394290931652222.45181692539550.782366266
#Sta/Elev= 30
       0  809.17    12.2     802    25.7  792.38    42.5  777.94    49.3  775.63
    76.3  776.92   106.6  774.03   133.6  780.13   167.4  779.67   177.5  776.82
   211.2  762.99   265.2  757.28  296.86756.8509   311.8  755.31   322.5  755.71
  325.66756.8502   331.7  759.91     344  762.87   361.4  764.45   383.9   764.5
   399.3  766.58   441.3  766.42     461  764.97     484  764.95   493.9  763.49
   533.4  766.71   691.6     769   714.3  772.17   730.7   778.1   772.3   790.5
#Mann= 7, -1 ,  0
       0     0.1       0      20    0.07       0  296.86   0.045       0
  325.66    0.07       0  338.69     0.1       0  443.84    0.05       0
  563.84     0.1       0
Bank Sta=296.86,325.66
XS Rating Curve= 0 ,0
Exp/Cntr(USF)=0,0
Exp/Cntr=0.3,0.1
LCMann Table=0

Chan Stop Cuts=-1
Use User Specified Reach Order=0
Composite Channel Slope=5